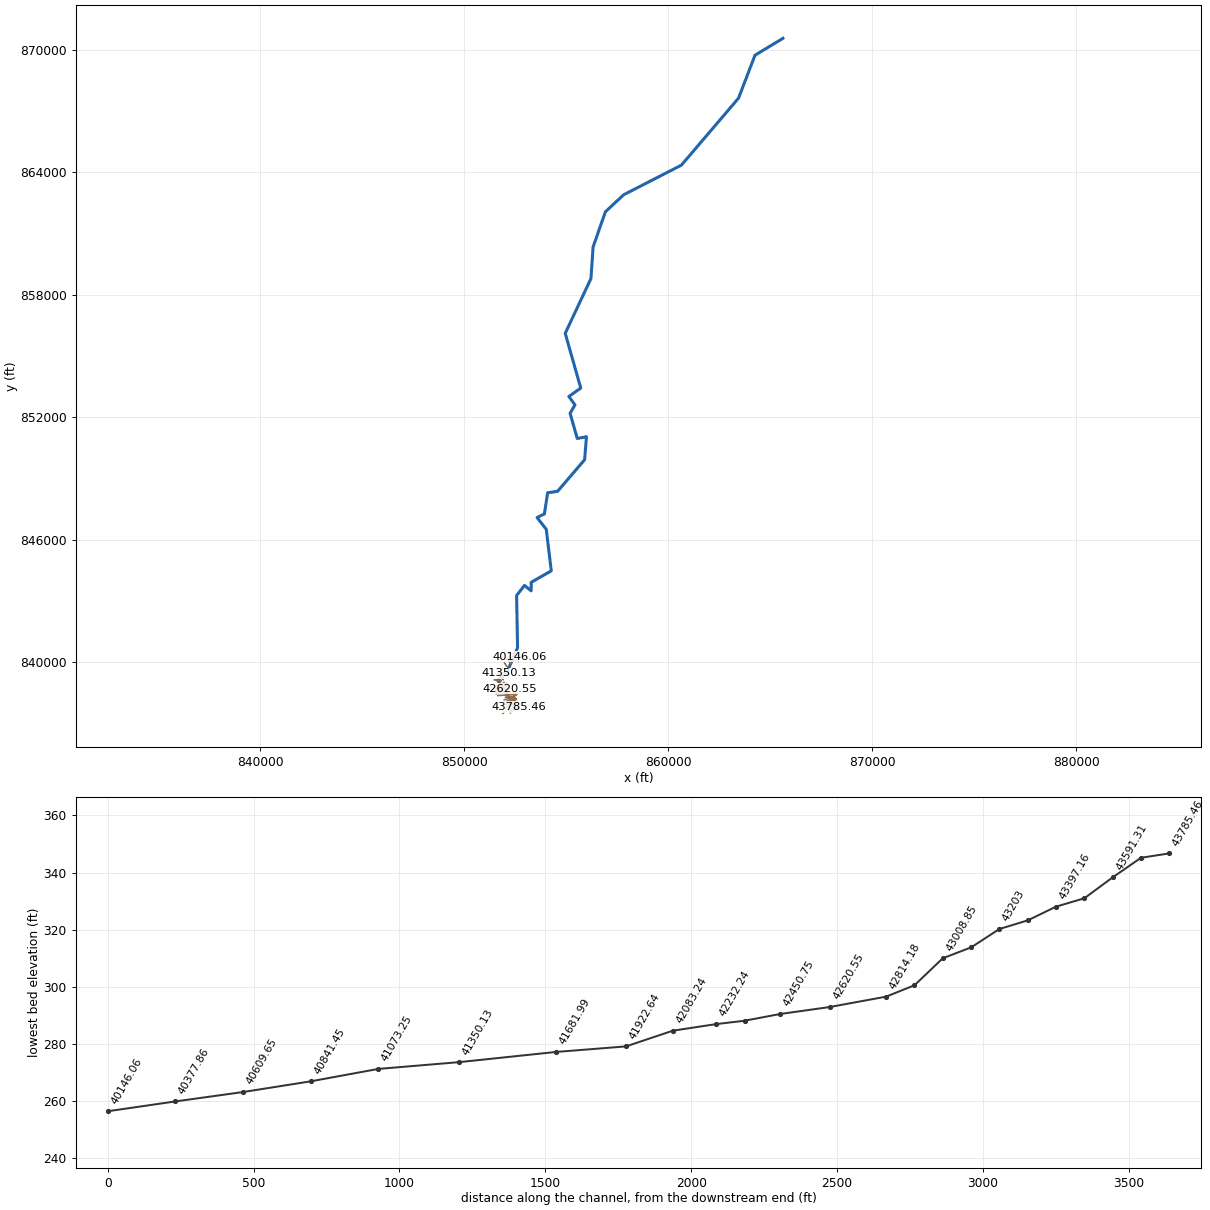
--- 18726_ras.prj (project) ---

Proj Title=18726
Current Plan=p01
Default Exp/Contr=0.3,0.1
English Units
Geom File=g01
Flow File=f01
Plan File=p01
Y Axis Title=Elevation
X Axis Title(PF)=Main Channel Distance
X Axis Title(XS)=Station
BEGIN DESCRIPTION:
RFD model 18726 exported to HEC-RAS
END DESCRIPTION:

--- 18726_ras.p01 (plan) ---

Plan Title=Plan 01
Program Version=4.10
Short Identifier=Plan 01
Geom File=g01
Flow File=f01
Subcritical Flow
Calc Critical at every XS
Secant Critical Depth

--- 18726_ras.f01 (steady flow) ---

Flow Title=Flow 01
Program Version=5.01
Number of Profiles= 6
Profile Names=10yr,25yr,50yr,100yr,100plus,500yr
River Rch & RM=18726,111,43785.46
 2520.22 3373.77 4063.27 4506.62 6579.66 6454.84
River Rch & RM=18726,111,43591.31
 2521.01 3374.94 4064.76 4508.36 6582.21 6457.27
River Rch & RM=18726,111,43494.23
 2523.36 3378.43 4069.23 4513.59 6589.85 6464.56
River Rch & RM=18726,111,43397.16
 2523.75 3379.01 4069.98 4514.47 6591.12 6465.77
River Rch & RM=18726,111,43300.08
 2526.11  3382.5 4074.45 4519.69 6598.75 6473.05
River Rch & RM=18726,111,   43203
 2926.23 3930.85 4745.51 5273.61 7699.47 7418.69
River Rch & RM=18726,111,43105.93
 2926.99 3931.98 4746.96  5275.3 7701.94 7420.99
River Rch & RM=18726,111,43008.85
 2927.37 3932.54 4747.68 5276.14 7703.17 7422.14
River Rch & RM=18726,111,42814.18
 2930.42 3937.05 4753.46  5282.9 7713.03 7431.33
River Rch & RM=18726,111,42620.55
 3041.11 4097.37 4956.36 5517.62 8055.72 7742.59
River Rch & RM=18726,111,42450.75
 3343.05 4530.61 5501.87 6145.96  8973.1 8558.52
River Rch & RM=18726,111,42329.32
  3344.9 4533.34 5505.37 6150.05 8979.07 8563.95
River Rch & RM=18726,111,42232.24
 3346.02 4534.98 5507.47  6152.5 8982.65 8567.21
River Rch & RM=18726,111,42083.24
 3364.67 4562.61  5542.9 6193.96 9043.19 8622.58
River Rch & RM=18726,111,41922.64
 3371.96 4573.42 5556.77  6210.2 9066.89 8644.25
River Rch & RM=18726,111,41681.99
 3390.63  4601.9 5593.93 6254.28 9131.25 8704.83
River Rch & RM=18726,111,41350.13
 3402.88 4620.28 5617.68 6282.25 9172.08  8742.6
River Rch & RM=18726,111,41073.25
 3412.29 4634.59 5636.31 6304.31 9204.29 8772.78
River Rch & RM=18726,111,40841.45
 3415.31 4639.19 5642.29  6311.4 9214.64 8782.47
River Rch & RM=18726,111,40609.65
 3427.07 4657.06 5665.55 6338.95 9254.86 8820.11
River Rch & RM=18726,111,40377.86
 3438.83 4674.91 5688.79 6366.47 9295.04 8857.69
River Rch & RM=18726,111,40146.06
 3600.21 4912.83 5993.32 6722.25 9814.48 9327.06
River Rch & RM=18726,111,39914.26
 3660.34 5002.77 6109.43 6858.8810013.96 9509.29
River Rch & RM=18726,111,39846.05
 3735.02 5114.75 6254.19 7029.4410262.99 9736.72
River Rch & RM=18726,111,39544.79
 3758.27 5150.34 6300.77 7084.86 10343.9 9812.06
River Rch & RM=18726,111,39375.96
 3769.21 5167.04 6322.56 7110.7510381.69 9847.08
River Rch & RM=18726,111,39140.91
 3790.37 5199.33 6364.73 7160.8610454.86 9914.91
River Rch & RM=18726,111,38905.87
 3807.48 5225.53 6399.02 7201.6710514.44 9970.27
River Rch & RM=18726,111,38670.82
 3813.83 5235.25 6411.73 7216.7910536.51 9990.75
River Rch & RM=18726,111,38435.78
 3820.17 5244.95 6424.42 7231.8910558.5610011.21
River Rch & RM=18726,111,38200.73
 3825.17 5252.63 6434.49  7243.9 10576.110027.56
River Rch & RM=18726,111,37965.69
 3829.05  5258.7 6442.51 7253.5310590.1510040.84
River Rch & RM=18726,111,37730.64
 4027.87 5566.74 6848.36 7739.3611299.4710704.35
River Rch & RM=18726,111,37449.84
 4035.29 5578.27 6863.57  7757.6 11326.110729.24
River Rch & RM=18726,111,37142.15
 4054.84 5608.65 6903.68  7805.711396.3210794.84
River Rch & RM=18726,111,36726.08
 4062.58 5620.64 6919.49 7824.6511423.9910820.63
River Rch & RM=18726,111,36555.41
 4064.34 5623.39 6923.12    782911430.3510826.58
River Rch & RM=18726,111,36506.44
 4095.58 5672.58 6988.53 7907.9211545.5610935.43
River Rch & RM=18726,111,36334.73
 4127.08 5722.45 7055.05 7988.3611663.0111046.81
River Rch & RM=18726,111,35868.31
 4131.47 5729.28 7064.08  7999.211678.8311061.57
River Rch & RM=18726,111,35318.58
 4153.01 5762.84 7108.45 8052.5111756.6611134.23
River Rch & RM=18726,111,35147.32
 4154.95 5765.91 7112.55 8057.47 11763.911141.09
River Rch & RM=18726,111,34950.41
  4159.1 5772.48 7121.33 8068.0911779.41 11155.8
River Rch & RM=18726,111,34678.43
 4416.67  6167.2 7638.84 8685.4612680.7711979.88
River Rch & RM=18726,111, 34423.3
 4420.24 6172.82 7646.33 8694.52   1269411992.27
River Rch & RM=18726,111,34203.44
 4421.87  6175.4 7649.77 8698.6912700.0811997.99
River Rch & RM=18726,111,33954.45
 4480.08 6268.13 7773.99 8849.5312920.3112205.83
River Rch & RM=18726,111,33705.46
 4500.52 6300.38 7816.96 8901.4912996.17 12276.7
River Rch & RM=18726,111,33456.47
 4507.65 6311.73 7832.19 8919.9913023.1812302.17
River Rch & RM=18726,111,33207.48
 4514.39 6322.54 7846.72 8937.6913049.0312326.68
River Rch & RM=18726,111,32958.49
 4530.48 6348.48 7881.69 8980.3813111.3612385.98
River Rch & RM=18726,111, 32709.5
 4535.08 6355.89 7891.68 8992.5813129.1612402.91
River Rch & RM=18726,111,32460.51
 4552.05 6383.44 7928.98 9038.2613195.8612466.76
River Rch & RM=18726,111,32211.52
 4560.44 6396.97 7947.23 9060.5413228.39 12497.7
River Rch & RM=18726,111,31962.52
  4565.4 6405.04 7958.16 9073.9413247.9512516.44
River Rch & RM=18726,111,31713.53
 4566.82 6407.39 7961.38 9077.9113253.7412522.06
River Rch & RM=18726,111,31464.54
 4573.78  6418.7 7976.69 9096.6713281.1312548.27
River Rch & RM=18726,111,31215.55
 4578.55 6426.56 7987.42 9109.8913300.4412566.98
River Rch & RM=18726,111,31059.67
 4579.26 6427.74 7989.03 9111.8713303.3312569.78
River Rch & RM=18726,111,31014.29
 4588.04 6442.24 8008.83  9136.3   1333912604.36
River Rch & RM=18726,111,30717.57
 4600.68 6463.22 8037.55 9171.78 13390.812654.76
River Rch & RM=18726,111,30468.58
 4603.53 6467.91 8043.96 9179.6913402.3512665.95
River Rch & RM=18726,111,30219.59
 4611.53 6481.16 8062.07 9202.0513434.9912697.63
River Rch & RM=18726,111, 29970.6
 4620.43 6496.05 8082.55 9227.4513472.0712733.93
River Rch & RM=18726,111,29721.61
 4625.33 6504.33 8093.99 9241.6713492.8412754.39
River Rch & RM=18726,111,29472.62
 4628.24 6509.23 8100.75 9250.0813505.1212766.47
River Rch & RM=18726,111,29223.63
 4637.82  6525.4 8123.08 9277.8613545.6812806.41
River Rch & RM=18726,111,28974.64
 4661.86 6565.53  8178.2 9346.1513645.3812903.73
River Rch & RM=18726,111,28725.65
 4670.68 6580.44 8198.83 9371.85 13682.912940.73
River Rch & RM=18726,111,28476.66
 4673.97 6586.02 8206.54 9381.4713696.9512954.59
River Rch & RM=18726,111,28227.67
 4679.44  6595.3  8219.4 9397.4913720.3412977.68
River Rch & RM=18726,111,27978.67
 4682.95 6601.25 8227.63 9407.7513735.3112992.46
River Rch & RM=18726,111,27729.68
 4726.35 6674.85 8329.56 9534.8713920.9113175.62
River Rch & RM=18726,111,27480.69
 4732.05 6684.62 8343.17 9551.9313945.82 13200.4
River Rch & RM=18726,111, 27231.7
 4737.85 6694.65 8357.18 9569.5313971.5113226.07
River Rch & RM=18726,111,26982.71
 4741.36 6700.71 8365.67 9580.1913987.0713241.65
River Rch & RM=18726,111,26733.72
 4771.74 6753.05 8438.73 9671.8814120.9513375.14
River Rch & RM=18726,111,26484.73
 4773.58 6756.24 8443.19  9677.514129.1513383.35
River Rch & RM=18726,111, 26309.1
 4781.23 6769.43 8461.63 9700.6514162.9613417.09
River Rch & RM=18726,111,26048.02
 4790.21    6785 8483.43 9728.08   1420313457.17
River Rch & RM=18726,111,25335.62
 4810.47 6820.19 8532.77 9790.2114293.7113548.08
River Rch & RM=18726,111,25017.69
 4814.59 6827.43 8542.98 9803.1314312.5713567.14
River Rch & RM=18726,111,24692.04
 4821.49 6839.54 8560.04 9824.6914344.0413598.89
River Rch & RM=18726,111,24362.14
 4823.85 6843.67 8565.87 9832.0714354.8213609.76
River Rch & RM=18726,111,23963.88
 4847.52 6885.29 8624.56 9906.3214463.2313719.25
River Rch & RM=18726,111, 23614.9
 4851.63 6892.51 8634.75  9919.214482.0413738.22
River Rch & RM=18726,111, 23295.7
 4857.29 6902.59 8649.06  9937.414508.61 13765.3
River Rch & RM=18726,111,22960.79
 4862.15 6911.29 8661.42 9953.1414531.5813788.75
River Rch & RM=18726,111,22658.55
 4865.14 6916.63 8669.03 9962.8214545.7113803.18
River Rch & RM=18726,111,21997.22
 4884.32 6950.82 8717.5710024.5514635.8513894.99
River Rch & RM=18726,111,21685.07
 4886.01 6953.82 8721.8410029.9914643.7913903.08
River Rch & RM=18726,111,21417.02
 4895.63 6971.07  8746.410061.2914689.4813949.78
River Rch & RM=18726,111,21198.33
 4904.87 6987.77 8770.2610091.7914734.0213995.53
River Rch & RM=18726,111,21023.64
 4905.41 6988.75 8771.6710093.5814736.6313998.22
River Rch & RM=18726,111,20541.55
 4910.64  6998.2 8785.1910110.89 14761.9 14024.2
River Rch & RM=18726,111,20059.46
 4920.18 7015.48 8809.91 10142.514808.0514071.64
River Rch & RM=18726,111,19479.66
 6583.87 9740.9312534.4714750.1921535.2820379.12
River Rch & RM=18726,111,18920.14
 6587.84 9747.8712544.29 14762.721553.55 20396.9
River Rch & RM=18726,111,17827.57
 6595.05 9760.4812562.1714785.5121586.8420429.37
River Rch & RM=18726,111,17180.51
 6674.65 9900.06 12760.315038.4121956.0720789.73
River Rch & RM=18726,111,16223.12
 6682.45 9913.8512779.9615063.5821992.8220825.78
River Rch & RM=18726,111,13350.96
 6719.89 9980.69 12875.715186.6722172.54 21003.4
River Rch & RM=18726,111,11436.19
 7369.1611119.6514495.3117258.7325197.7423938.64
River Rch & RM=18726,111,7606.643
 9572.3614805.7319619.1723703.3734606.9232472.56
River Rch & RM=18726,111,4734.483
 9808.9815231.0620234.7424503.8835775.67 33585.2
River Rch & RM=18726,111,1862.324
 10325.716163.2921587.6826267.9538351.2136034.01
River Rch & RM=18726,111,      -0
10453.1116395.8621927.4926713.5539001.7936656.38
Boundary for River Rch & Prof#=18726,111,1
Up Type= 0
Dn Type= 2
Boundary for River Rch & Prof#=18726,111,2
Up Type= 0
Dn Type= 2
Boundary for River Rch & Prof#=18726,111,2
Up Type= 0
Dn Type= 2
Boundary for River Rch & Prof#=18726,111,2
Up Type= 0
Dn Type= 2
Boundary for River Rch & Prof#=18726,111,2
Up Type= 0
Dn Type= 2
Boundary for River Rch & Prof#=18726,111,2
Up Type= 0
Dn Type= 2

--- 18726_ras.g01 (geometry) ---

Geom Title=18726
Program Version=4.10

River Reach=18726,111
Reach XY= 30
852545.206407116837736.235725484851641.079823954839114.398576829
852072.116166719 839429.39340713852620.076462608840697.337621362
852571.735217052843257.837465191852959.198712631 843751.48828463
853284.835755589843485.511161746853289.035908733843904.246373756
854269.933827642844465.704881757854026.512154907846498.037989237
853575.742056179847077.852578154853932.452896719 847252.80406325
854094.068683334848290.515525698854582.247662728 848364.32708596
855905.121367684849909.484288966855994.319439281851035.774493919
855544.256865961850951.774664964855192.917434645852184.687579379
855431.490873642852597.400600214  855132.4048054 853008.19272108
855714.980039797853419.062148243854954.818403284856102.969292637
856214.531814144858785.315523264856320.520354668 860334.41698399
856921.936102151862056.212726991857815.342535125862889.492339033
860644.613900102864341.238161021863444.670226848867622.861879973
864251.686536521869727.056485045865620.437660047870555.490209369

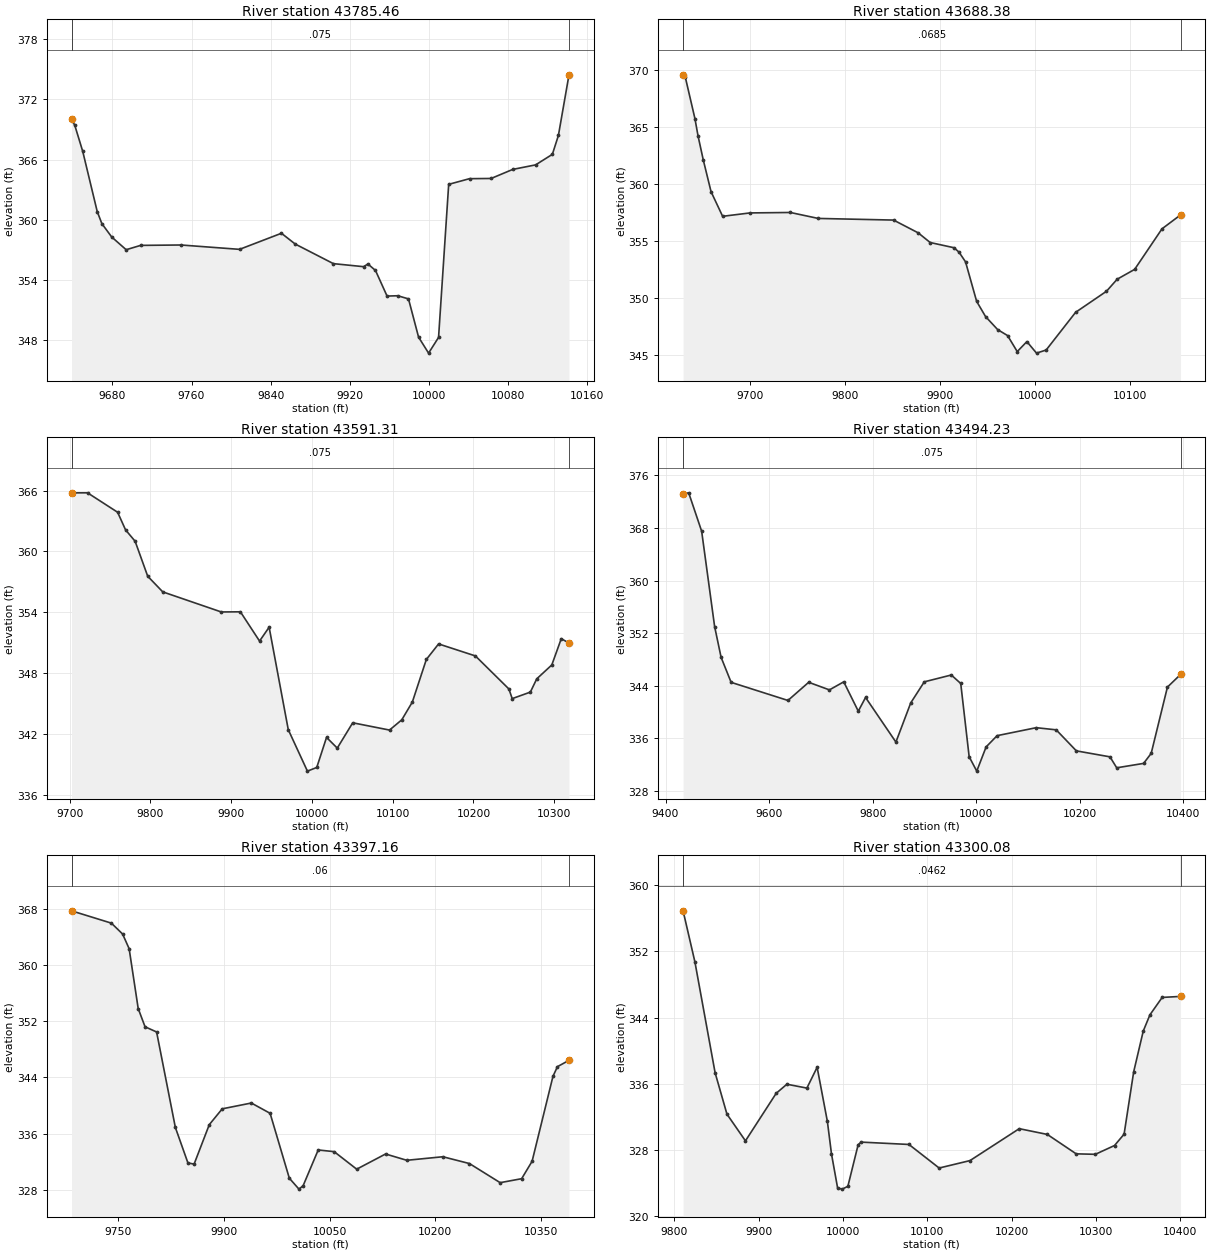
Type RM Length L Ch R = 1 ,43785.46,97.076100,97.076100,97.076100
XS GIS Cut Line= 6
852272.593773023837507.241107502852484.807630807837712.393300552
852525.529626845837733.904293699852578.484550208837744.390098592
852623.101968123837763.946104905852674.285550317837793.392092575
#Sta/Elev= 30
9638.588370.04229641.883 369.4139649.945366.81319664.583360.82489669.271359.6241
 9679.22358.29339693.858357.02439708.495357.4559 9749.34357.49479808.591357.0606
9850.983358.66359864.892357.59079903.563355.63649934.075355.33439938.489355.6007
9946.155354.95659957.855352.40639968.701352.43739979.547352.12419989.735348.3142
9999.876346.720310009.97 348.28610020.22 363.538 10041.3364.102910063.14364.1235
10085.02365.025910108.17365.477710125.12366.527910131.24368.411810141.95374.4507
#Mann= 3 , 0 , 0
9638.588   0.075       09638.588   0.075       010141.95   0.075       0
#XS Ineff= 2 , 0
       09872.546                       0
Bank Sta=9638.588,10141.95
Exp/Cntr=0.3,0.1

Type RM Length L Ch R = 1 ,43688.38,97.076100,97.076100,97.076100
XS GIS Cut Line= 6
852263.248205117837516.687763273852383.536373855837635.447526411
852460.927601004  837729.1412438852481.760760509837769.335830489
852502.522730911837861.027103165852550.902119872837941.035136353
#Sta/Elev= 30
9629.489369.60729631.838369.39789641.961365.76929645.251364.24529650.709 362.158
9658.944359.35739671.134357.19669699.961357.49359742.479357.53299771.833357.0109
9851.198356.86679877.155355.74579889.754354.89849914.953354.43919920.171  354.05
 9927.02353.2019 9938.71349.73829948.087348.40389960.864347.2581 9971.32 346.734
 9981.48345.33059991.639346.206310001.79345.195510011.93345.468410042.95 348.774
 10075.5350.622710086.75351.679110105.15352.541810133.96356.0985 10153.5357.3178
#Mann= 3 , 0 , 0
9629.489  0.0685       09629.489  0.0685       0 10153.5  0.0685       0
#XS Ineff= 2 , 0
       09861.675        10060.22       0
Bank Sta=9629.489,10153.5
Exp/Cntr=0.3,0.1

Type RM Length L Ch R = 1 ,43591.31,97.076000,97.076000,97.076000
XS GIS Cut Line= 5
852234.366264036837568.573421918852393.632204981837818.865455471
852394.621747784837820.603501828852400.129983318 837830.96793758
852601.289974975 838061.01776992
#Sta/Elev= 30
9702.332365.7799 9722.14365.78429759.394363.86749769.214362.13159781.067361.0083
9796.649357.55759815.276356.01499887.743354.03449911.448354.04889935.154 351.162
9947.007352.53189970.713342.42379994.418338.335910005.98338.696510018.09341.6603
10031.38340.607210050.52 343.10410096.09342.386310111.29343.397410124.36345.1514
10141.67349.348110156.86 350.88110202.44349.697110243.92346.437610248.01 345.487
10270.49346.129910278.39347.437210297.05348.808510308.78351.401210318.33350.9654
#Mann= 3 , 0 , 0
9702.332   0.075       09702.332   0.075       010318.33   0.075       0
#XS Ineff= 2 , 0
       09913.997         10070.5       0
Bank Sta=9702.332,10318.33
Exp/Cntr=0.3,0.1

Type RM Length L Ch R = 1 ,43494.23,97.076100,97.076100,97.076100
XS GIS Cut Line= 6
851906.352722382837482.839944516852041.168007994837587.462693838
852177.795729447837713.047927164852280.029739006837830.219011764
852391.302626272837974.786033688852561.154985486838179.958173941
#Sta/Elev= 30
9433.893373.19389444.716373.3498 9469.75367.50689494.783353.0108  9507.3348.3229
9526.664344.5175 9636.38341.7626 9676.43344.5256 9716.48343.37029744.147344.5942
9772.234340.13049786.277342.21819844.881335.42869873.518341.3904 9899.68344.5956
9951.817 345.6359970.074 344.3459986.321333.2052   10001331.010810019.07334.6928
10040.32336.407210115.86337.620510154.43337.291610193.37334.091910258.28333.1838
10271.27331.516810323.19332.186210337.84333.708710369.21343.793810394.54 345.712
#Mann= 3 , 0 , 0
9433.893   0.075       09433.893   0.075       010394.54   0.075       0
#XS Ineff= 2 , 0
       09938.784        10051.27       0
Bank Sta=9433.893,10394.54
Exp/Cntr=0.3,0.1

Type RM Length L Ch R = 1 ,43397.16,97.076100,97.076100,97.076100
XS GIS Cut Line= 6
852001.381439589837729.485871721852085.859190608 837797.65747595
852172.214065604837873.460705365852239.596242082837935.888752111
852334.150207737838023.915218667852527.090978585838200.335117755
#Sta/Elev= 30
9683.684367.76029740.236366.00449756.159364.45089765.434362.35939778.284 353.827
9788.006351.22719804.401350.48549831.013336.87359848.843331.81449857.626331.6475
 9879.16337.27049897.544 339.5289938.836340.3562 9965.47338.88939992.734329.6385
10006.42 328.07810012.33328.564610033.74 333.66210056.38333.420910088.37330.9223
10129.34333.088810159.43332.189510210.64332.695310248.35331.725110291.94328.9995
10322.44329.565910337.26332.0473 10366.9344.165110373.24345.539310389.63346.4438
#Mann= 3 , 0 , 0
9683.684    0.06       09683.684    0.06       010389.63    0.06       0
#XS Ineff= 2 , 0
       09953.858        10042.75       0
Bank Sta=9683.684,10389.63
Exp/Cntr=0.3,0.1

Type RM Length L Ch R = 1 ,43300.08,97.076100,97.076100,97.076100
XS GIS Cut Line= 6
 852023.29940991837906.359818012852221.461878442 838041.30753873
852277.275694793838077.619578962852390.734330543838145.511256016
852491.975564568838200.098773394852524.596845856838215.995090913
#Sta/Elev= 30
9810.277356.89159824.294350.72149848.254337.3228 9862.29332.32379884.234 329.096
 9920.66334.84039933.362335.94029957.087335.47229969.229337.99029981.371331.4477
9986.253327.51559993.514323.3992    9999323.264110005.67323.604110017.84  328.62
10021.41328.945410078.12328.660810113.91325.814210150.47326.7116 10208.9330.5686
10242.16329.873810276.41327.527410299.13327.471510321.86328.533910333.22329.9064
10344.58337.436710355.94 342.36610363.86344.326210378.35346.427310400.15346.5501
#Mann= 3 , 0 , 0
9810.277  0.0462       09810.277  0.0462       010400.15  0.0462       0
#XS Ineff= 2 , 0
       09953.505        10052.18       0
Bank Sta=9810.277,10400.15
Exp/Cntr=0.3,0.1

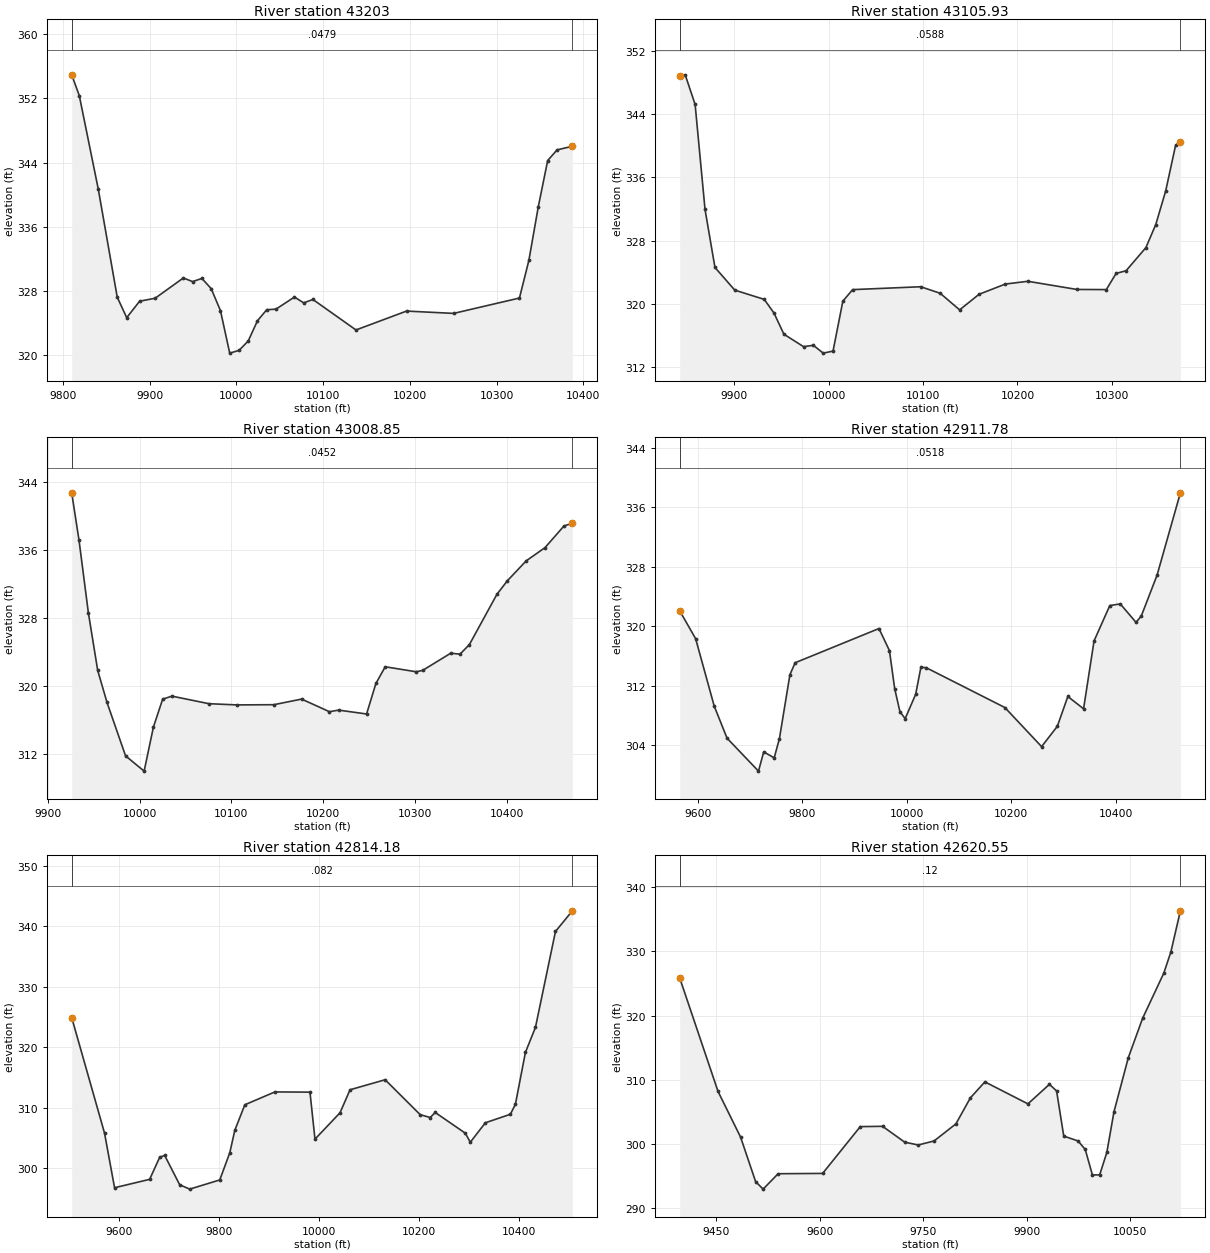
Type RM Length L Ch R = 1 ,   43203,97.076000,97.076000,97.076000
XS GIS Cut Line= 6
851957.146950978838023.042287938851970.279428864838029.423006152
852065.700360501838071.230609173852133.077373966838096.888370172
852241.595162242838136.745913533852491.230871746838241.681740233
#Sta/Elev= 30
9810.123354.93079818.854352.34929840.795340.6708 9862.63327.21899873.548324.6644
9888.457326.71699906.301327.08359938.848329.61139949.544 329.159 9960.24329.5555
9970.936328.28659981.632325.54559992.328320.244710003.05320.5842 10013.7321.7637
10024.35324.284710035.01325.653810045.66325.725810066.97327.233510077.62 326.509
10088.27326.931310137.91323.132510196.23325.486110250.47325.1962 10326.4327.1119
10337.25331.7942 10348.1338.472210358.95344.246410369.79345.5766 10387.4346.0258
#Mann= 3 , 0 , 0
9810.123  0.0479       09810.123  0.0479       0 10387.4  0.0479       0
#XS Ineff= 2 , 0
       0 9956.02        10067.24       0
Bank Sta=9810.123,10387.4
Exp/Cntr=0.3,0.1

Type RM Length L Ch R = 1 ,43105.93,97.076100,97.076100,97.076100
XS GIS Cut Line= 6
851959.471253476838145.895159796852013.072623951838162.965322007
852131.357537729838196.946062706852292.010111679838236.352615651
852401.559518533838266.727169976852469.831964287838288.381220621
#Sta/Elev= 30
9842.473348.78599848.275 348.931 9858.77345.19039869.265331.9355 9879.76324.6219
9900.732321.75689931.944320.58819942.348318.84879952.752316.1898 9973.56  314.62
9983.964314.79169994.368313.803310004.78314.059610015.18320.363910025.55 321.819
10097.62322.182510118.21321.359310138.81319.2641 10159.4321.231210187.21 322.521
10211.07322.870810262.95321.839710294.09321.8228 10304.5323.868710314.99324.1995
10335.98327.115110346.47330.035610356.96334.275210367.45340.026510372.52340.4761
#Mann= 3 , 0 , 0
9842.473  0.0588       09842.473  0.0588       010372.52  0.0588       0
#XS Ineff= 2 , 0
       09953.859        10056.37       0
Bank Sta=9842.473,10372.52
Exp/Cntr=0.3,0.1

Type RM Length L Ch R = 1 ,43008.85,97.076100,97.076100,97.076100
XS GIS Cut Line= 6
852017.193361794838273.692913673852089.011666262838285.366653639
852314.487443088838314.253861899852388.041857587838326.571064423
852449.762450241838339.095185338852553.900669681838364.360948878
#Sta/Elev= 30
9926.217342.75799934.186 337.1769944.394 328.6059954.513321.85359964.621318.0883
9984.837 311.79410005.04 309.99810015.12315.1722 10025.2318.469510035.28318.8255
10075.61317.934210105.85317.793310146.18317.817310176.43318.477810206.67316.9928
10216.75317.180310247.12316.724210257.26320.3173 10267.4322.2824 10300.9321.6976
   10308321.847310338.61323.873410348.81323.770710359.02 324.89810388.92330.8066
10400.14 332.38210420.72334.7426 10441.3336.309510461.88338.848210471.04339.1935
#Mann= 3 , 0 , 0
9926.217  0.0452       09926.217  0.0452       010471.04  0.0452       0
#XS Ineff= 2 , 0
       0                10043.97       0
Bank Sta=9926.217,10471.04
Exp/Cntr=0.3,0.1

Type RM Length L Ch R = 1 ,42911.78,97.600100,97.600100,97.600100
XS GIS Cut Line= 5
851644.664639972838350.205508209852075.702478571838381.597051173
852077.280965358838381.754392063852079.271404408838381.949718567
852599.488564856838430.650402543
#Sta/Elev= 30
9565.234322.0627 9595.65318.32949631.242309.26989655.809 304.9629715.968300.5365
9725.994303.12339746.047302.31829756.074304.90699776.127313.48279786.153315.0926
9946.577319.6881 9966.63316.72089976.656  311.629986.683308.52139996.709307.5828
 10016.8 310.84910026.84314.482410036.88314.431610187.54309.079310257.85303.8283
10287.98306.555610308.07310.5596 10338.2308.910110358.28 318.02910388.42322.7747
 10408.5322.993810438.63320.512910448.68321.374210478.81326.845510523.49337.9137
#Mann= 3 , 0 , 0
9565.234  0.0518       09565.234  0.0518       010523.49  0.0518       0
#XS Ineff= 2 , 0
       09950.813        10045.83       0
Bank Sta=9565.234,10523.49
Exp/Cntr=0.3,0.1

Type RM Length L Ch R = 1 ,42814.18,193.628100,193.628100,193.628100
XS GIS Cut Line= 2
851579.455059121838447.295325795852578.674557268838511.824509775
#Sta/Elev= 30
9505.548324.90829571.229305.79669591.271296.77369661.417298.15899681.458301.7918
9691.479302.12079721.542297.26369741.583296.54389801.708298.0644 9821.75302.5617
9831.771306.26429851.813310.48529911.938312.61039982.083312.57479992.104304.8057
10042.21309.166610062.25312.9678 10132.4314.622810202.54308.850610222.58 308.382
 10232.6309.214210292.73305.790410302.75304.294810332.81307.508610382.92308.9164
10392.94310.564310412.98319.141910433.02323.2704 10473.1339.133310506.85342.5416
#Mann= 3 , 0 , 0
9505.548   0.082       09505.548   0.082       010506.85   0.082       0
#XS Ineff= 2 , 0
       0 9961.58        10083.16       0
Bank Sta=9505.548,10506.85
Exp/Cntr=0.3,0.1

Type RM Length L Ch R = 1 ,42620.55,169.798200,169.798200,169.798200
XS GIS Cut Line= 6
851573.993161892838453.944279677851755.421774824838531.463596361
851929.452426878838597.765846263851995.804822653838618.682589232
852140.661259755838658.800119595852258.414715943838688.024188939
#Sta/Elev= 30
 9397.52325.85739452.988308.14979485.612301.02789507.361294.08969518.236292.9083
9539.985295.3109 9604.39 295.3599658.928 302.6639691.211302.70899723.303300.2315
9742.894299.79919765.745300.42319797.382303.09439818.352307.15389839.322309.6455
 9901.66306.21439932.767309.26429943.136308.22989953.504301.18139974.242300.4253
9984.611299.0983 9994.98295.1233 10005.5295.128510015.86298.626210026.22304.9772
10046.95313.412210067.67319.565810098.39326.625410108.63 329.93610122.36336.3386
#Mann= 3 , 0 , 0
 9397.52    0.12       0 9397.52    0.12       010122.36    0.12       0
#XS Ineff= 2 , 0
       09930.472                       0
Bank Sta=9397.52,10122.36
Exp/Cntr=0.3,0.1

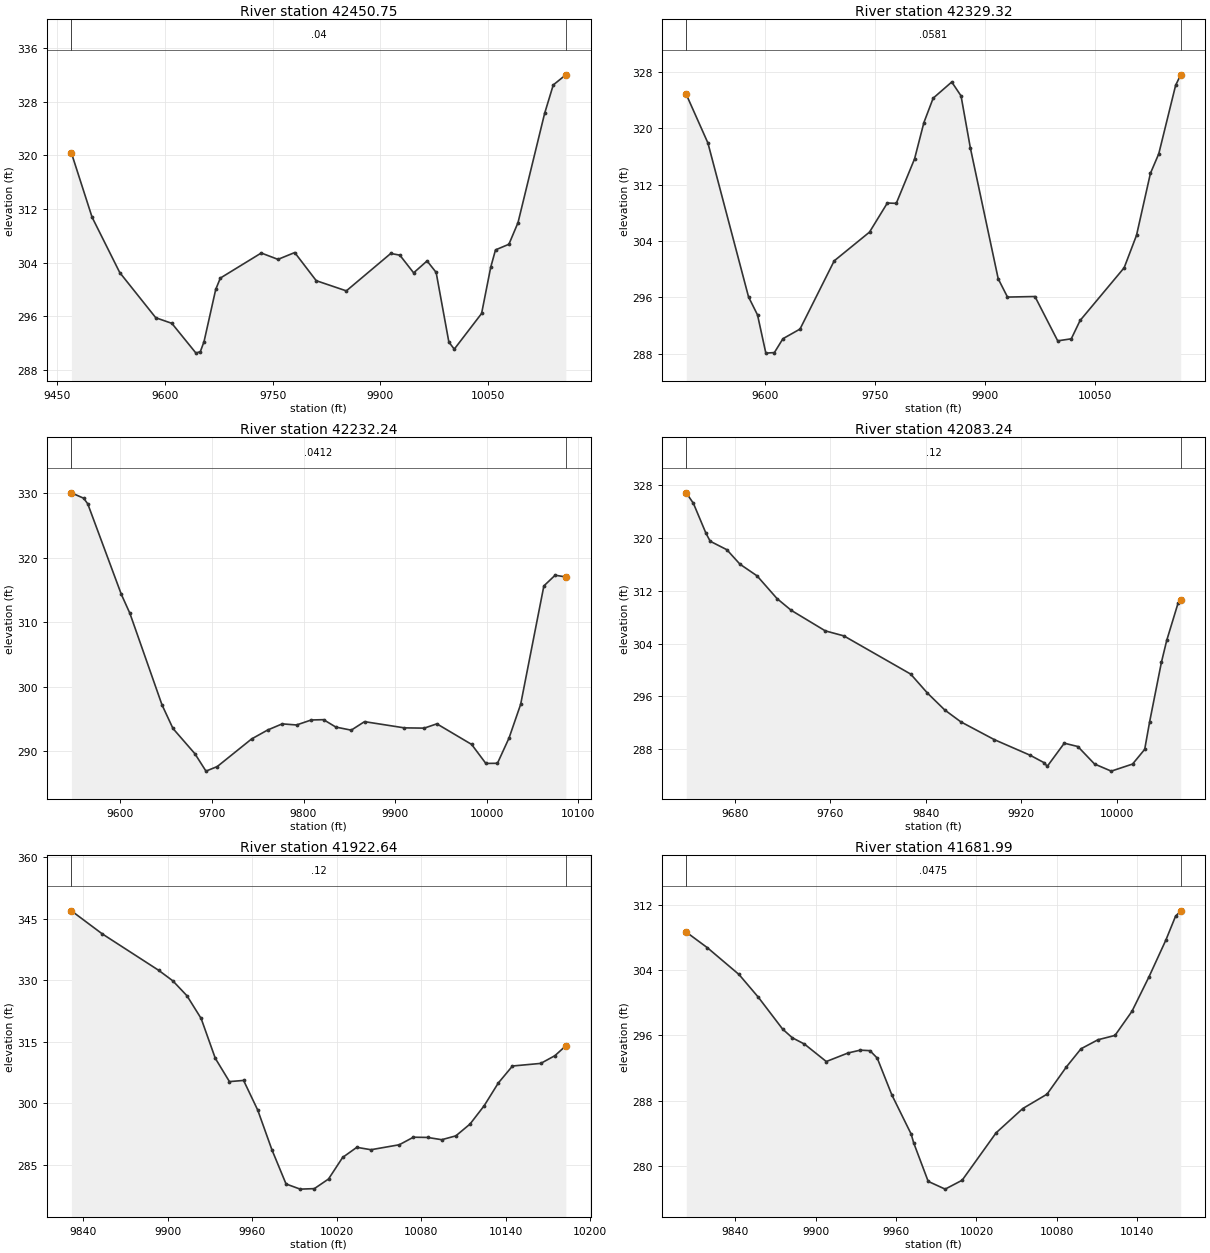
Type RM Length L Ch R = 1 ,42450.75,121.430000,121.430000,121.430000
XS GIS Cut Line= 6
851558.945427245838496.132601459851727.555785661838578.595792551
851858.289234621838653.386449926851923.755682777838699.051369034
852099.605820394838835.708011817852139.511888039838862.520285147
#Sta/Elev= 30
9469.587320.3852 9498.42310.77339536.989302.50329587.164295.75589609.587294.9171
9643.222290.46929649.347 290.7089654.434 292.1969670.705299.98629677.155301.6817
9734.166 305.4259757.482304.47559780.797305.49479810.767301.29219852.706299.7694
9914.632305.35759927.278305.10569946.493302.46349965.217304.24069977.863302.5311
9995.592292.124610003.13291.063910041.19296.389510053.88303.285710060.58305.8907
10079.26306.732410091.94309.964510129.02 326.28110141.07330.533710158.55332.0441
#Mann= 3 , 0 , 0
9469.587    0.04       09469.587    0.04       010158.55    0.04       0
#XS Ineff= 2 , 0
       09968.025                       0
Bank Sta=9469.587,10158.55
Exp/Cntr=0.3,0.1

Type RM Length L Ch R = 1 ,42329.32,97.076100,97.076100,97.076100
XS GIS Cut Line= 6
 851518.47113604838586.593103283 851614.18024287838635.587889845
851704.964046955838689.812247866 851772.43184546838736.558548533
851948.289772903838871.203606325852081.014105606838955.362252497
#Sta/Elev= 30
9492.161324.76269521.676317.87789577.059296.0822 9589.31293.52789600.651288.1178
9612.299288.19819623.947290.16049647.243291.52759693.835301.18659741.982305.2577
9766.314309.3818 9778.48309.33079803.443315.64139816.111320.76449828.779324.2288
9854.115326.52019866.783324.55289879.452317.19689917.456298.64869930.124296.0566
9967.564296.13639998.574289.857610017.08290.1458 10029.1292.739910089.19300.2124
10106.02304.802710124.98313.579110136.36316.352410159.35 326.05210166.26327.5358
#Mann= 3 , 0 , 0
9492.161  0.0581       09492.161  0.0581       010166.26  0.0581       0
#XS Ineff= 2 , 0
       09952.852                       0
Bank Sta=9492.161,10166.26
Exp/Cntr=0.3,0.1

Type RM Length L Ch R = 1 ,42232.24,149.003100,149.003100,149.003100
XS GIS Cut Line= 6
851529.262549498838668.690142141 851611.16995744 838715.36465217
851686.342821994838767.120759349851771.698803658838839.633607719
851863.701094001838927.296508839851954.592857739838997.495333566
#Sta/Elev= 30
9546.621330.10129559.987329.26639564.473328.39559601.057 314.3819610.473311.4094
9645.502297.22099657.473293.55799681.415289.64079693.507286.94119705.854287.6561
 9743.31291.93199760.758293.31369776.727294.27039792.324294.09919808.409294.8733
9821.831294.92079835.254293.77259852.025 293.2949866.521294.6155 9910.01293.6508
9931.681293.60899945.494294.27539983.424291.08279998.945288.134810011.61288.1584
10024.28292.089310036.94297.306810062.27315.666610074.57317.325610086.21317.0557
#Mann= 3 , 0 , 0
9546.621  0.0412       09546.621  0.0412       010086.21  0.0412       0
#XS Ineff= 2 , 0
       09894.725                       0
Bank Sta=9546.621,10086.21
Exp/Cntr=0.3,0.1

Type RM Length L Ch R = 1 ,42083.24,160.596000,160.596000,160.596000
XS GIS Cut Line= 2
  851513.5494696838770.710460626851803.189364944839066.543576843
#Sta/Elev= 30
9639.492 326.8829645.495325.2729 9655.86320.7954 9659.49 319.5349673.485318.2437
9684.448316.04729698.742314.2793 9715.47310.8291 9727.33309.04829755.919 305.922
9771.449305.16139827.389299.36229841.424296.47929855.977 293.9059869.413292.1088
9897.403289.41159927.448287.03859939.388285.88219941.742285.34449956.036288.8676
9967.378288.36229981.373285.70699995.367284.626210013.21285.700210023.36287.9311
10027.51292.128610037.35301.1369 10041.8304.469410051.35310.160810053.51310.5541
#Mann= 3 , 0 , 0
9639.492    0.12       09639.492    0.12       010053.51    0.12       0
#XS Ineff= 2 , 0
       09880.519                       0
Bank Sta=9639.492,10053.51
Exp/Cntr=0.3,0.1

Type RM Length L Ch R = 1 ,41922.64,240.650300,240.650300,240.650300
XS GIS Cut Line= 2
851473.310923944839123.901847185851822.689511939839091.182050112
#Sta/Elev= 30
9831.753346.96759853.537341.37799893.712332.46559903.756329.8984  9913.8326.2547
9923.844320.72279933.887311.01959943.931305.33699953.975305.62249964.019298.3839
9974.062288.73079984.106280.3833 9994.15279.125310004.19279.245510014.24281.5901
10024.28286.853110034.32 289.31510044.37 288.73110064.46289.9403 10074.5291.7823
10084.54291.727210094.59 291.17310104.63292.112210114.68294.989510124.72299.4581
10134.76305.002710144.81309.139910164.89309.774810174.94311.663610182.66314.0597
#Mann= 3 , 0 , 0
9831.753    0.12       09831.753    0.12       010182.66    0.12       0
#XS Ineff= 2 , 0
       0                               0
Bank Sta=9831.753,10182.66
Exp/Cntr=0.3,0.1

Type RM Length L Ch R = 1 ,41681.99,331.860600,331.860600,331.860600
XS GIS Cut Line= 2
851690.834460721839417.462890294851917.370581596839126.293213298
#Sta/Elev= 30
9803.528308.64449819.318 306.7299842.881303.45499857.329300.66599875.452296.7652
9882.669295.70399891.737 294.9339908.009292.79789924.307 293.8499933.349294.1918
9940.592294.1292 9946.02293.21839956.877288.7259 9971.36283.90459973.162282.8645
 9984.03278.1252  9996.7277.174910009.37278.263510034.71284.069910054.59287.0402
10072.72288.802810087.16292.139810098.06294.359710110.73295.4657 10123.4295.9941
10136.07 298.94310148.74303.154210161.41307.682910168.58 310.58110172.44311.2508
#Mann= 3 , 0 , 0
9803.528  0.0475       09803.528  0.0475       010172.44  0.0475       0
#XS Ineff= 2 , 0
       0                               0
Bank Sta=9803.528,10172.44
Exp/Cntr=0.3,0.1

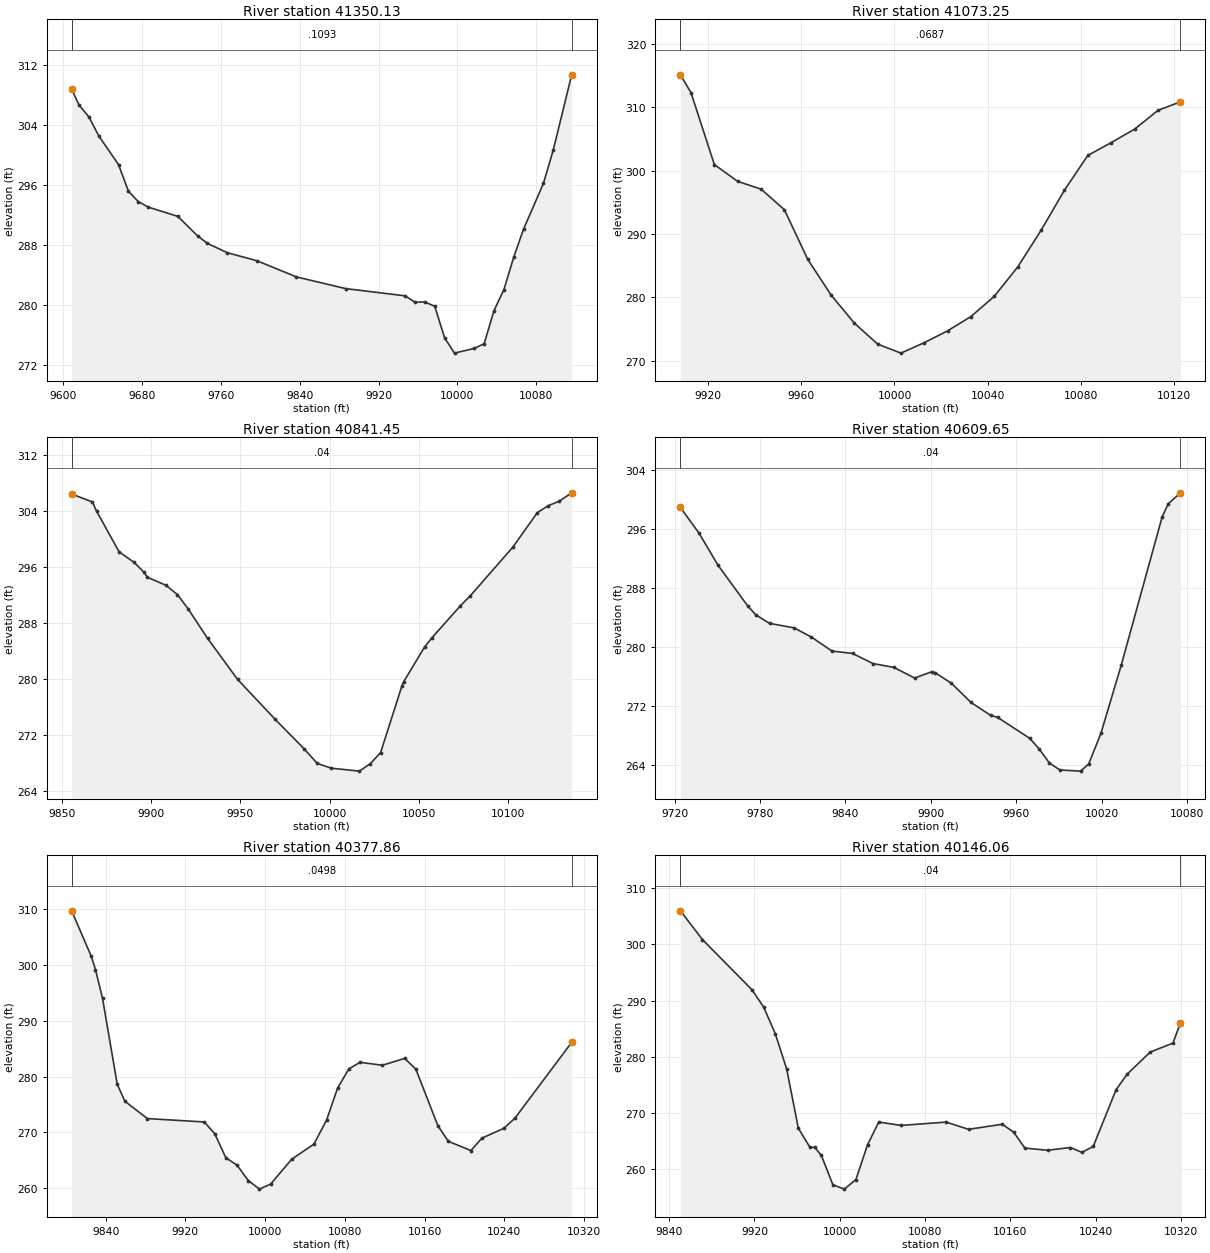
Type RM Length L Ch R = 1 ,41350.13,276.882500,276.882500,276.882500
XS GIS Cut Line= 2
851687.548060513839480.946594616852193.556129204839440.518719763
#Sta/Elev= 30
9608.395308.8027 9615.87306.68339625.902305.11089635.934302.56739655.998298.7447
 9666.03295.19689676.062293.81089686.094293.08349716.189291.84319736.253289.2381
9746.285288.23669766.348287.00329796.444285.93019836.572283.77389886.731282.2101
9946.922281.24979956.954280.40249966.986280.42989977.018279.8528 9987.05275.6308
9997.081273.609910017.15274.237510027.18274.866910037.21279.290810047.24282.0784
10057.27286.4319 10067.3290.185510087.37296.2466 10097.4300.725210116.02310.7203
#Mann= 3 , 0 , 0
9608.395  0.1093       09608.395  0.1093       010116.02  0.1093       0
#XS Ineff= 2 , 0
       09788.712                       0
Bank Sta=9608.395,10116.02
Exp/Cntr=0.3,0.1

Type RM Length L Ch R = 1 ,41073.25,231.798600,231.798600,231.798600
XS GIS Cut Line= 6
851830.529070536839667.715094609 851836.66085051839666.663900479
851891.841152321839662.422986468851921.232235533839661.885287979
851950.900871894839662.630534943852044.594489358839671.777521617
#Sta/Elev= 23
 9908.04 315.0839912.576312.28359922.625300.94189932.654298.29119942.684 297.075
9952.713293.83289962.743286.00399972.763280.39039982.765275.96029992.767272.6536
10002.77271.234410012.77272.879110022.78274.7384 10032.8276.987910042.85280.1725
 10052.9284.792410062.96290.575110073.01296.905810083.06302.384810093.11304.4032
10103.16306.523610113.22 309.48910122.83310.8266
#Mann= 3 , 0 , 0
 9908.04  0.0687       0 9908.04  0.0687       010122.83  0.0687       0
#XS Ineff= 2 , 0
       0                               0
Bank Sta=9908.04,10122.83
Exp/Cntr=0.3,0.1

Type RM Length L Ch R = 1 ,40841.45,231.798500,231.798500,231.798500
XS GIS Cut Line= 6
851967.285261334839955.420504391851990.534789129839929.325852743
852026.302644579839880.876266642852075.013761009839804.160314134
 852104.08873927839768.125320486852140.712037053 839737.40360825
#Sta/Elev= 30
9855.472306.47779867.069305.35429869.428304.03289882.101298.20829890.421296.7249
9895.798295.36089897.939294.58349908.228293.45099914.776292.10499920.658290.1074
9931.613285.8701 9948.45     2809969.429274.31469985.622270.11459993.093267.9865
   10001267.304610016.78266.884610022.93267.962510028.65269.545110040.52 279.008
10041.49  279.6310053.29284.622910057.42285.943110073.35290.505710078.99291.9573
10102.77298.895610116.46303.817910122.59304.811610128.73305.449210135.73 306.652
#Mann= 3 , 0 , 0
9855.472    0.04       09855.472    0.04       010135.73    0.04       0
#XS Ineff= 2 , 0
       0                               0
Bank Sta=9855.472,10135.73
Exp/Cntr=0.3,0.1

Type RM Length L Ch R = 1 ,40609.65,231.798500,231.798500,231.798500
XS GIS Cut Line= 6
852044.791180497840165.853684463852050.933144692840161.020934448
852098.837307816840119.238596887852144.824712149 840075.23235212
852242.156005359839971.977386645852294.087363663839918.963685074
#Sta/Elev= 30
9724.071298.86269737.283295.33619750.552 291.0179771.473 285.4849777.091284.3016
9786.687283.16079803.981282.54569816.046281.3068 9830.51279.40779844.974 279.084
9859.358277.71119873.935277.19839888.513275.75449900.652276.60939903.091276.4622
9914.396275.04339928.139272.45039941.883270.70099946.823270.4258 9969.37267.5889
9975.979266.15849983.113264.26189990.556263.295610005.07263.141510010.75264.0964
10019.39268.252910033.71277.524310062.35297.556810066.63299.349210075.22300.8435
#Mann= 3 , 0 , 0
9724.071    0.04       09724.071    0.04       010075.22    0.04       0
#XS Ineff= 2 , 0
       0                               0
Bank Sta=9724.071,10075.22
Exp/Cntr=0.3,0.1

Type RM Length L Ch R = 1 ,40377.86,231.798500,231.798500,231.798500
XS GIS Cut Line= 6
852207.471582532840245.941170443    852379.10564840157.508143885
852380.899332641840156.623459363 852513.91197166840089.317461294
852616.375629815840041.341747097852657.007982997 840023.50365492
#Sta/Elev= 30
9805.923309.68279825.641301.51539829.811299.16799836.891294.00589851.644278.6194
9859.389275.57479881.888272.48739938.977271.87599949.384269.79549960.633265.4711
9971.883264.14039983.132261.38659994.381259.8527 10005.6260.760810026.74265.2164
10048.89267.892810061.63272.190410072.84277.990510084.05 281.37210095.25282.5607
10117.67282.032610140.08283.256110151.27281.319410173.36 271.20110183.84268.4133
10206.48 266.75910217.52268.981410239.61 270.74910250.65272.553310307.59286.1224
#Mann= 3 , 0 , 0
9805.923  0.0498       09805.923  0.0498       010307.59  0.0498       0
#XS Ineff= 2 , 0
       0                10090.13       0
Bank Sta=9805.923,10307.59
Exp/Cntr=0.3,0.1

Type RM Length L Ch R = 1 ,40146.06,231.798500,231.798500,231.798500
XS GIS Cut Line= 6
852282.692078259840432.852249429852420.020998632840376.500204982
852421.906746775840375.833906331852445.096397592840366.073874853
 852571.72198122840324.249552365852721.546323935840267.983992291
#Sta/Elev= 30
9850.559305.99129871.243300.87079917.909291.88459928.718288.81019939.527284.1154
9950.268277.79469961.145267.28619971.954263.8921 9976.61 263.8439982.764262.4224
9993.573257.190910004.36256.418110015.21258.132910026.06 264.30210036.59268.3636
10057.65267.764210099.78268.357210120.84267.070610152.43267.974210163.02266.5865
 10173.7263.723510195.06263.344210216.43263.831710227.11262.964510237.79264.0167
10259.15274.106510269.83276.9387 10291.2280.826410312.56  282.4310319.56286.0181
#Mann= 3 , 0 , 0
9850.559    0.04       09850.559    0.04       010319.56    0.04       0
#XS Ineff= 2 , 0
       0                10047.74       0
Bank Sta=9850.559,10319.56
Exp/Cntr=0.3,0.1