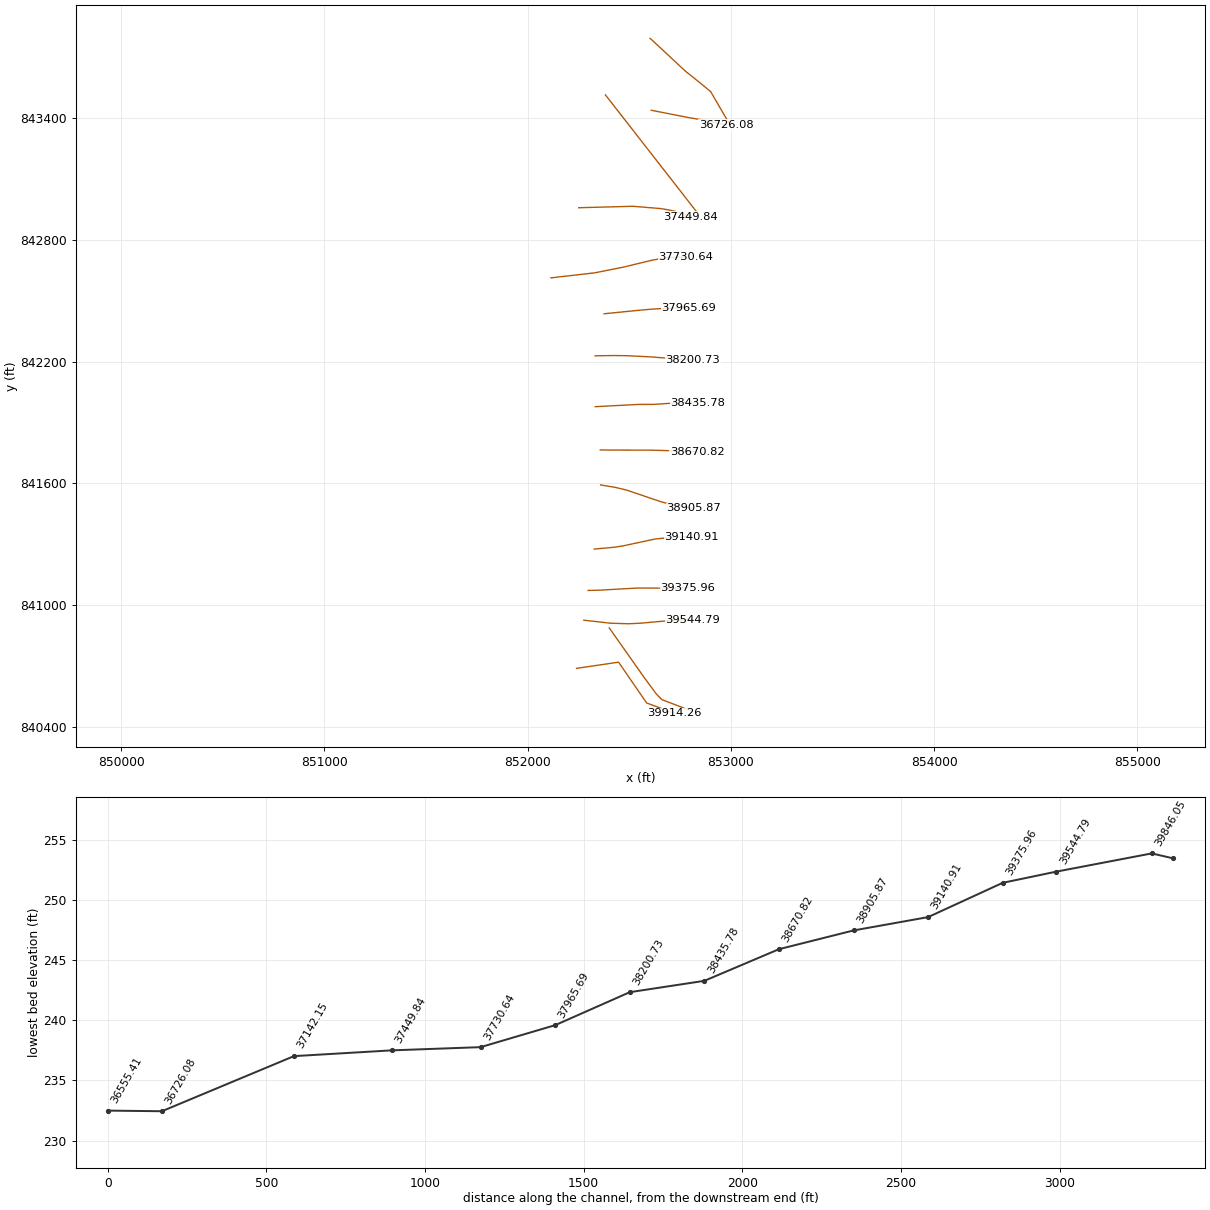
HEC-RAS study 18726_ras.prj: 18726

--- 18726_ras.g01 (geometry) --- (continued)

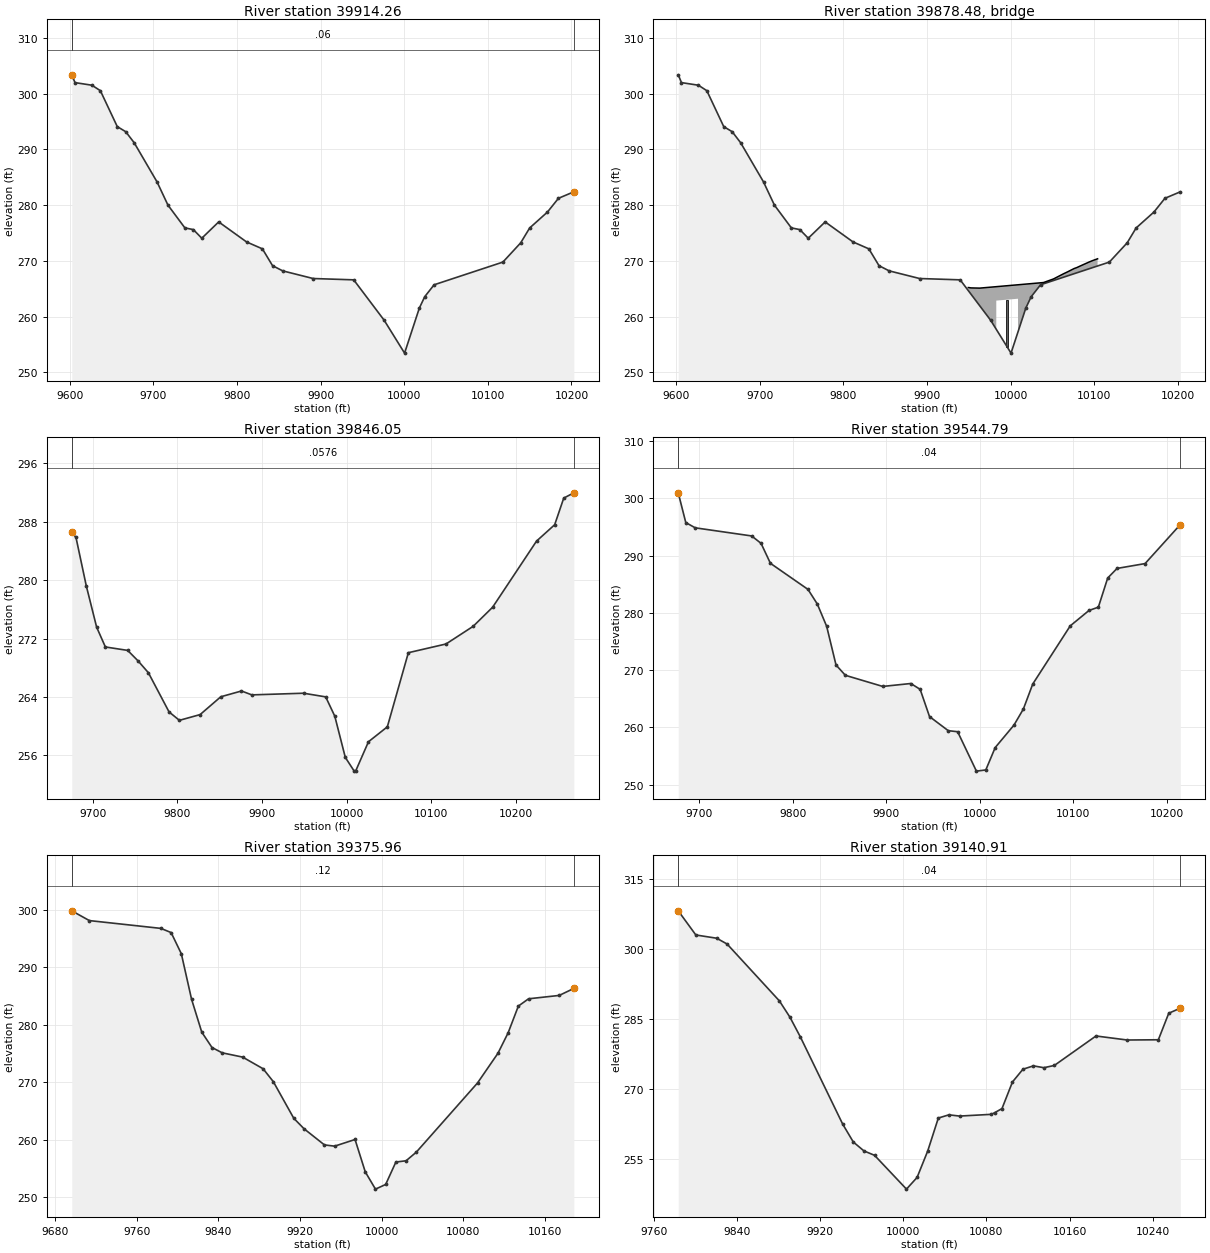
Type RM Length L Ch R = 1 ,39914.26,68.209300,68.209300,68.209300
XS GIS Cut Line= 4
852241.161126047840690.126343191852447.975371838840720.616192222
852585.962135196840519.805710003852724.592265487840468.621159941
#Sta/Elev= 30
9602.405303.35129606.285301.95469626.501301.4881 9636.61 300.5059656.826294.0636
9666.934293.15189677.042291.17229704.384284.14899717.474279.9749 9737.69275.9006
9747.799275.59649757.907274.04829778.123 276.9749811.455273.38259830.402272.1415
9842.536269.12259854.669268.19419891.069266.82079939.602266.58399976.002259.3435
10000.43253.440910018.09261.517310024.54263.561510035.75265.696810118.04269.7691
10139.36273.226110150.02275.885110171.34278.743410184.47281.207610202.88282.3711
#Mann= 3 , 0 , 0
9602.405    0.06       09602.405    0.06       010202.88    0.06       0
#XS Ineff= 2 , 0
       09956.981        10033.86       0
Bank Sta=9602.405,10202.88
Exp/Cntr=0.3,0.1

Type RM Length L Ch R = 3 ,39878.48,,,
BEGIN DESCRIPTION:
END DESCRIPTION:
Bridge Culvert--1,0,-1,-1, 0
Deck Dist Width WeirC Skew NumUp NumDn MinLoCord MaxHiCord MaxSubmerge Is_Ogee
26.104650,16.000000,2.6,0, 20, 20, , , 0.95, 0, 0,0,,
 9949.32 9950.37 9952.24 9962.92 9962.95 9982.78 9982.7810008.7810008.7810039.28
10050.7710051.5410063.3110068.0910075.8610079.1810082.7710093.6510097.8610103.96
  265.20  265.19  265.14  265.10  265.10  265.36  265.36  265.70  265.70  266.10
  266.72  266.77  267.68  268.02  268.61  268.79  269.04  269.77  270.03  270.36
 -734.80 -734.81 -734.86 -734.90 -734.90 -734.64  262.86  263.20 -734.30 -733.90
 -733.28 -733.23 -732.32 -731.98 -731.39 -731.21 -730.96 -730.23 -729.97 -729.64
 9949.32 9950.37 9952.24 9962.92 9962.95 9994.75 9994.7510020.7510020.7510039.28
10050.7710051.5410063.3110068.0910075.8610079.1810082.7710093.6510097.8610103.96
  265.20  265.19  265.14  265.10  265.10  265.52  265.52  265.86  265.86  266.10
  266.72  266.77  267.68  268.02  268.61  268.79  269.04  269.77  270.03  270.36
 -734.80 -734.81 -734.86 -734.90 -734.90 -734.48  263.02  263.36 -734.14 -733.90
 -733.28 -733.23 -732.32 -731.98 -731.39 -731.21 -730.96 -730.23 -729.97 -729.64
Pier Skew, UpSta & Num, DnSta & Num=  ,9995.78, 2 ,10007.75, 2 , 0 , 0 , 0 ,,
    2.00    2.00
 -734.47  265.53
    2.00    2.00
 -734.31  265.69
BR Coef=-1 , 0 , 0 ,, 0 ,,,0.8,0,1,0,
WSPro=,,,, 1 ,,,, 0 ,,,, 0 ,,,,-1 ,-1 ,-1 , 0 , 0 , 0 , 0 , 0
BC Design=,, 0 ,, 0 ,,,,,,

Type RM Length L Ch R = 1 ,39846.05,301.259800,301.259800,301.259800
XS GIS Cut Line= 5
852402.129743601840889.027765616852573.207984814840646.096270016
 852634.29293555840563.212216891 852660.91672756840536.258973896
852806.154412982840480.671045766
#Sta/Elev= 30
9675.116 286.5589680.101285.85359692.273279.22629704.504273.57319714.837 270.859
9741.196270.38959753.427268.95889765.658 267.337 9790.12261.96469802.351 260.814
9826.812261.59969851.274264.04139875.735264.83199887.966264.2984 9949.12264.5262
9975.262264.02519986.026261.38269998.448255.740610008.97253.859610010.87253.9217
10025.83257.881410048.14259.925910072.98270.073510117.46271.266410149.58273.6856
10172.56276.295510224.53285.358410245.95287.596310256.66291.2419 10268.6291.9632
#Mann= 3 , 0 , 0
9675.116  0.0576       09675.116  0.0576       0 10268.6  0.0576       0
#XS Ineff= 2 , 0
       09970.635        10044.37       0
Bank Sta=9675.116,10268.6
Exp/Cntr=0.3,0.1

Type RM Length L Ch R = 1 ,39544.79,168.831200,168.831200,168.831200
XS GIS Cut Line= 6
852277.004162046840927.129724458852408.471128643840912.306586727
852497.615811194840909.577016264852553.838189373840912.192049839
852727.616418492840927.706990707852812.689932661840928.730955794
#Sta/Elev= 30
9677.385300.96239685.465295.7662 9695.57294.84849755.975 293.4299766.024292.1375
9776.074 288.6459816.244284.09459826.248281.53589836.253277.64059846.258270.8891
9856.263269.08419896.281267.14029926.312 267.6529936.323266.63089946.334261.8752
9966.396259.41149976.443259.22899996.537252.344610006.58252.550710016.64256.4628
10036.74260.385710046.79263.195110056.85267.564810096.98277.723510117.03280.4102
10127.05280.986510137.06286.082210147.06287.755710177.07288.602710214.77 295.414
#Mann= 3 , 0 , 0
9677.385    0.04       09677.385    0.04       010214.77    0.04       0
#XS Ineff= 2 , 0
       09929.562                       0
Bank Sta=9677.385,10214.77
Exp/Cntr=0.3,0.1

Type RM Length L Ch R = 1 ,39375.96,235.045400,235.045400,235.045400
XS GIS Cut Line= 6
852297.754119797841073.444079266852352.856757339841074.795913243
852540.851800842841085.336026832852600.179404852 841085.33757819
852661.488687494 841084.85504075852789.356179777841087.396507236
#Sta/Elev= 30
9696.263299.86539713.514298.16589783.576296.80769793.592 296.0829803.607292.3956
9813.623284.48269823.639278.74169833.654276.0698 9843.67275.14339863.701274.3998
9883.733272.37029893.749270.1246 9913.78 263.7529923.796261.93129943.821259.1138
9953.821258.89559973.821260.05579983.821254.42469993.821251.415210003.82 252.228
10013.82256.130610023.82256.351110033.82257.847110093.83269.900410113.83275.0652
10123.84278.637710133.84283.283710143.84 284.55210173.85285.1367 10188.2286.3562
#Mann= 3 , 0 , 0
9696.263    0.12       09696.263    0.12       0 10188.2    0.12       0
#XS Ineff= 2 , 0
       0                               0
Bank Sta=9696.263,10188.2
Exp/Cntr=0.3,0.1

Type RM Length L Ch R = 1 ,39140.91,235.045500,235.045500,235.045500
XS GIS Cut Line= 6
852328.100897837841277.019380204852428.438200665841286.315679905
 852471.40297791841293.136683849852627.954393164 841326.65212594
 852725.42014227841336.103190476852806.123361379841337.446357707
#Sta/Elev= 30
9783.456308.09639800.398302.93119820.448302.23639830.473300.99399880.785288.8293
9890.889 285.3619901.014281.10099941.657262.48499951.887258.64839962.117256.7438
9972.347 255.79810003.05248.567810013.27251.070310023.49 256.72310033.71263.7769
10043.94264.459510054.16264.193810084.83264.566310087.85264.911410094.95265.7966
10105.02271.4851 10115.1274.214110125.17274.933210135.25274.5401 10145.3 275.021
10185.39281.326510215.39280.4645 10245.4 280.516 10255.4286.187910266.52287.2772
#Mann= 3 , 0 , 0
9783.456    0.04       09783.456    0.04       010266.52    0.04       0
#XS Ineff= 2 , 0
       0                               0
Bank Sta=9783.456,10266.52
Exp/Cntr=0.3,0.1

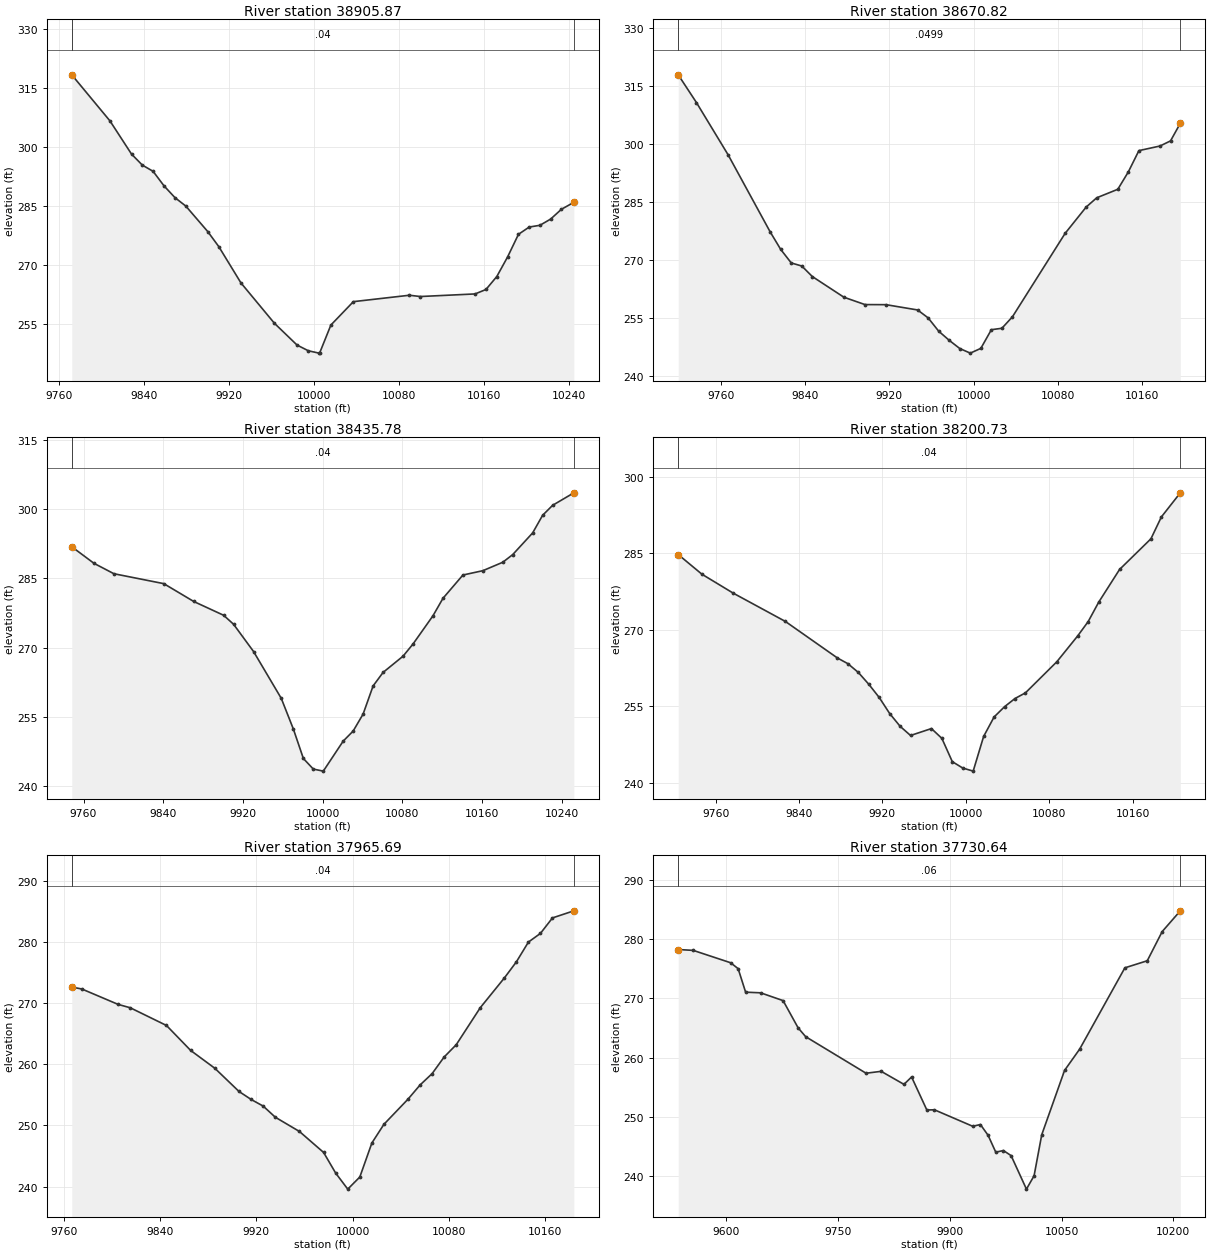
Type RM Length L Ch R = 1 ,38905.87,235.045500,235.045500,235.045500
XS GIS Cut Line= 6
 852359.50486619841592.642492101852431.509092033841580.653232973
852488.213611246841567.178607423852655.263430562841510.280600286
852701.757328332841497.537611781852816.588352817841476.929992208
#Sta/Elev= 30
9772.168318.31169808.145306.57399828.426298.13449838.566295.33769848.755  293.74
9859.034290.03939869.312287.0513 9879.59284.88789900.147278.42249910.551274.5925
9931.475  265.339963.002255.05069984.275249.51649994.912248.057210004.95247.4592
10005.54247.484910016.13 254.60710037.31 260.56610090.05262.194610100.42261.8692
10151.93262.530710162.15263.662210172.37266.967710182.59271.988610192.75277.7081
10202.86279.558410212.96280.006310223.07 281.59110233.18284.080510244.89285.8518
#Mann= 3 , 0 , 0
9772.168    0.04       09772.168    0.04       010244.89    0.04       0
#XS Ineff= 2 , 0
       0                               0
Bank Sta=9772.168,10244.89
Exp/Cntr=0.3,0.1

Type RM Length L Ch R = 1 ,38670.82,235.045500,235.045500,235.045500
XS GIS Cut Line= 6
852357.674995426841765.029126681852394.620983393841764.413683103
852609.482058399841763.725445029852637.151347919841762.994405692
852743.325333176841759.938928626852834.269826866841755.109707926
#Sta/Elev= 30
9719.508317.83359736.835310.65159766.838297.17649806.838277.22569816.838272.7028
9826.838269.21089836.838268.41629846.838265.69649876.839260.35159896.839258.4513
9916.839258.42469946.839257.05789956.839255.00589966.839251.57529976.841249.2121
9986.844247.09539996.848245.902510006.86 247.13410016.86251.956710026.86 252.327
10036.87255.291210086.89276.8527 10106.9283.659310116.91286.051410136.94288.2506
10146.95292.754610156.97298.2432   10177299.436510187.01300.760910196.29 305.311
#Mann= 3 , 0 , 0
9719.508  0.0499       09719.508  0.0499       010196.29  0.0499       0
#XS Ineff= 2 , 0
       0                               0
Bank Sta=9719.508,10196.29
Exp/Cntr=0.3,0.1

Type RM Length L Ch R = 1 ,38435.78,235.045400,235.045400,235.045400
XS GIS Cut Line= 6
852332.706834519841977.707468361852542.792400047841988.690114166
852618.725868927841988.924224775852724.340293501 841995.79700014
852805.551675353841998.361857442852836.360004207841998.095299631
#Sta/Elev= 30
9748.169291.87039770.475288.28359790.502286.02869840.577283.88139870.622280.0228
9900.667277.03199910.682275.07949930.712269.18329958.546259.04049970.753252.3593
9980.754246.00959990.754 243.71410000.76243.273710020.76249.777610030.76251.9571
10040.77255.641210050.79 261.72910060.81 264.65410080.85268.167510090.87 270.808
10110.92276.924910120.94280.700310140.98 285.74810160.99286.6865   10181288.5118
   10191290.174710211.01294.869510221.02298.687210231.02300.840510252.38303.5516
#Mann= 3 , 0 , 0
9748.169    0.04       09748.169    0.04       010252.38    0.04       0
#XS Ineff= 2 , 0
       0                               0
Bank Sta=9748.169,10252.38
Exp/Cntr=0.3,0.1

Type RM Length L Ch R = 1 ,38200.73,235.045500,235.045500,235.045500
XS GIS Cut Line= 6
852332.267570603842227.780729545852341.335610762842228.148414363
852422.581208156842229.415925108852491.509141286842228.561324616
852606.967694672842222.667509597852813.092963173842206.795661209
#Sta/Elev= 30
9724.127284.73619746.868280.88529776.872277.18139826.878271.64339876.881264.4781
9886.887263.3652  9896.9261.65289906.913259.34019916.926256.74979926.939253.6117
9936.952251.11049946.965249.31179966.991250.66329977.004248.75229987.017244.1859
 9997.03242.936610007.05242.331310017.08249.126210027.11252.933610037.14254.9463
10047.17256.5504 10057.2257.659710087.29 263.74610107.35268.818310117.38271.6184
10127.41275.396610147.47281.816910177.56287.823810187.59292.106110205.74296.8233
#Mann= 3 , 0 , 0
9724.127    0.04       09724.127    0.04       010205.74    0.04       0
#XS Ineff= 2 , 0
       0                               0
Bank Sta=9724.127,10205.74
Exp/Cntr=0.3,0.1

Type RM Length L Ch R = 1 ,37965.69,235.045500,235.045500,235.045500
XS GIS Cut Line= 6
852376.655537222842434.914839387852559.126587881842453.192313972
852609.982881754842457.483238194852681.639013606842461.878717319
852749.726082691842463.615825719852792.759036842842462.902180238
#Sta/Elev= 30
9766.579272.63639774.965272.31499805.115269.79729815.165269.24989845.315266.3512
9865.415262.26959885.516259.35239905.616255.55829915.666254.25659925.716253.1672
9935.766251.35119955.857249.01719975.928245.58829985.964242.21319995.999239.5929
10006.03241.574710016.05247.135910026.06250.1899 10046.1254.306510056.12256.6228
10066.14258.480910076.15261.201310086.16263.201710106.16269.258910126.17 274.117
10136.17276.753610146.17279.986710156.18281.408710166.18283.939710183.94285.0972
#Mann= 3 , 0 , 0
9766.579    0.04       09766.579    0.04       010183.94    0.04       0
#XS Ineff= 2 , 0
       0                               0
Bank Sta=9766.579,10183.94
Exp/Cntr=0.3,0.1

Type RM Length L Ch R = 1 ,37730.64,280.800000,280.800000,280.800000
XS GIS Cut Line= 6
852114.925374904842611.583579572852329.683662723842636.242826292
852471.138082129842664.210577778852612.713166612842698.605300751
852686.705300896842711.275534055 852779.32359845842714.197530275
#Sta/Elev= 30
9535.376278.26659555.513 278.1229605.711276.03199615.776 275.035 9625.84271.0575
9645.968270.95049676.161269.62799696.351265.01859706.457263.53339787.493257.3583
9807.812257.67689838.396 255.4759848.626256.72399869.088251.14899879.319251.1731
9930.713248.38889941.015248.68539951.317246.86989961.619244.01739971.921244.2868
9982.222243.430110002.82237.765910013.08240.026410023.34246.952910053.99257.8349
10074.28261.435910134.95275.172310165.02276.368910185.03281.298210209.37284.8084
#Mann= 3 , 0 , 0
9535.376    0.06       09535.376    0.06       010209.37    0.06       0
#XS Ineff= 2 , 0
       0 9871.06                       0
Bank Sta=9535.376,10209.37
Exp/Cntr=0.3,0.1

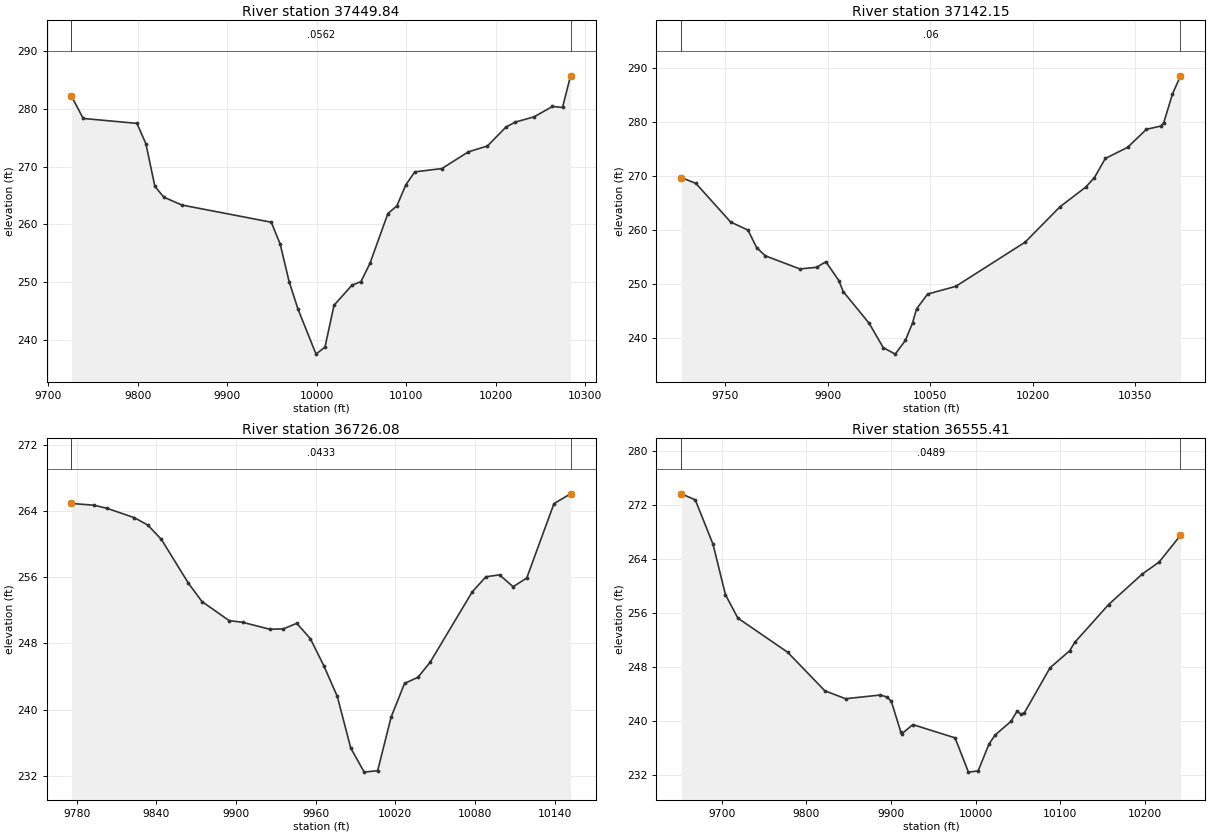
Type RM Length L Ch R = 1 ,37449.84,307.692300,307.692300,307.692300
XS GIS Cut Line= 6
852251.895326448842956.694939626 852518.54410282842963.832822813
852656.453636147842952.392741583852694.210547981842946.174802878
852725.687295662842938.860599584852803.363569881842912.983145639
#Sta/Elev= 30
9726.039282.23289739.147278.37389799.179277.51949809.185 273.978 9819.19266.6025
9829.196264.72519849.207263.36449949.259260.37769959.259256.55879969.259  250.04
9979.259 245.2479999.282237.497610009.32238.732610019.36245.976410039.43249.4484
10049.46250.0719 10059.5 253.22910079.56261.8823 10089.6263.205610099.63266.8696
10109.66269.112510139.85  269.6810169.45272.5787 10190.8273.598310211.53276.8865
10222.02277.748310242.98278.658410263.39280.4512 10274.7280.292210283.68285.7688
#Mann= 3 , 0 , 0
9726.039  0.0562       09726.039  0.0562       010283.68  0.0562       0
#XS Ineff= 2 , 0
       0                               0
Bank Sta=9726.039,10283.68
Exp/Cntr=0.3,0.1

Type RM Length L Ch R = 1 ,37142.15,416.072700,416.072700,416.072700
XS GIS Cut Line= 2
852383.308288551843511.852382873852832.631960231842935.687294902
#Sta/Elev= 30
 9685.88269.65969707.251268.56639757.977261.44249783.339 259.9539796.021 256.714
9808.702255.19519859.427252.76569883.766253.07269897.472254.10139916.288250.6238
9922.834248.58339960.878242.70069981.333 238.2289998.922237.018710013.86239.5688
10024.29242.778610030.12245.374110046.38248.120510087.69 249.55610189.14257.7189
10239.87264.228410277.91 267.90310290.59269.655210306.56273.194410339.08275.2407
10366.68278.576210387.86279.186610392.04279.790210404.73285.062710416.54288.4676
#Mann= 3 , 0 , 0
 9685.88    0.06       0 9685.88    0.06       010416.54    0.06       0
#XS Ineff= 2 , 0
       09934.193                       0
Bank Sta=9685.88,10416.54
Exp/Cntr=0.3,0.1

Type RM Length L Ch R = 1 ,36726.08,170.662400,170.662400,170.662400
XS GIS Cut Line= 6
852608.547735198843436.360962724852795.602849675843399.616771129
852835.574090367843393.010564722852837.555047631843392.735246067
852873.943793157 843387.15398157852977.189429495843363.772225967
#Sta/Elev= 30
9776.172264.92189792.939264.7124 9803.13264.32569823.512263.20219833.703262.3037
9843.894260.57019864.277255.26249874.468253.0623 9894.85250.76339905.041250.5544
9925.423249.71919935.614249.75569945.805250.43269955.996248.58969966.188245.3052
9976.327241.59719986.462 235.3529996.598232.441510006.73 232.61810016.85239.0911
10026.96243.160710037.08243.909510046.13 245.69910077.97254.242710088.23256.0569
10098.48256.291710108.73254.855710118.99255.911710139.49264.902810151.99266.0873
#Mann= 3 , 0 , 0
9776.172  0.0433       09776.172  0.0433       010151.99  0.0433       0
#XS Ineff= 2 , 0
       09942.008         10061.7       0
Bank Sta=9776.172,10151.99
Exp/Cntr=0.3,0.1

Type RM Length L Ch R = 1 ,36555.41,48.973000,48.973000,48.973000
XS GIS Cut Line= 6
852602.739838043843790.207230713852614.529634853843779.724003403
852779.467707279843626.244205782852816.561736027843597.293350821
852900.771216305843528.587775205 852997.71939905843361.766455351
#Sta/Elev= 30
9652.206273.72599668.625272.83339689.597266.25469704.276258.78049718.956255.3124
9777.674250.26489821.713244.54569846.202243.36789887.181 243.9199895.306243.6193
9900.302242.96969911.559238.41539912.987238.20199925.672 239.5389975.603237.5695
9991.421232.493510002.85 232.67310015.76236.662910023.06238.004910041.57240.0015
10049.02241.551610053.17241.070710057.44241.260210087.87247.9542   10111250.4703
10117.14251.730910156.95257.309510196.75261.835510216.65263.608210241.97267.5643
#Mann= 3 , 0 , 0
9652.206  0.0489       09652.206  0.0489       010241.97  0.0489       0
#XS Ineff= 2 , 0
       09836.915        10065.79       0
Bank Sta=9652.206,10241.97
Exp/Cntr=0.3,0.1