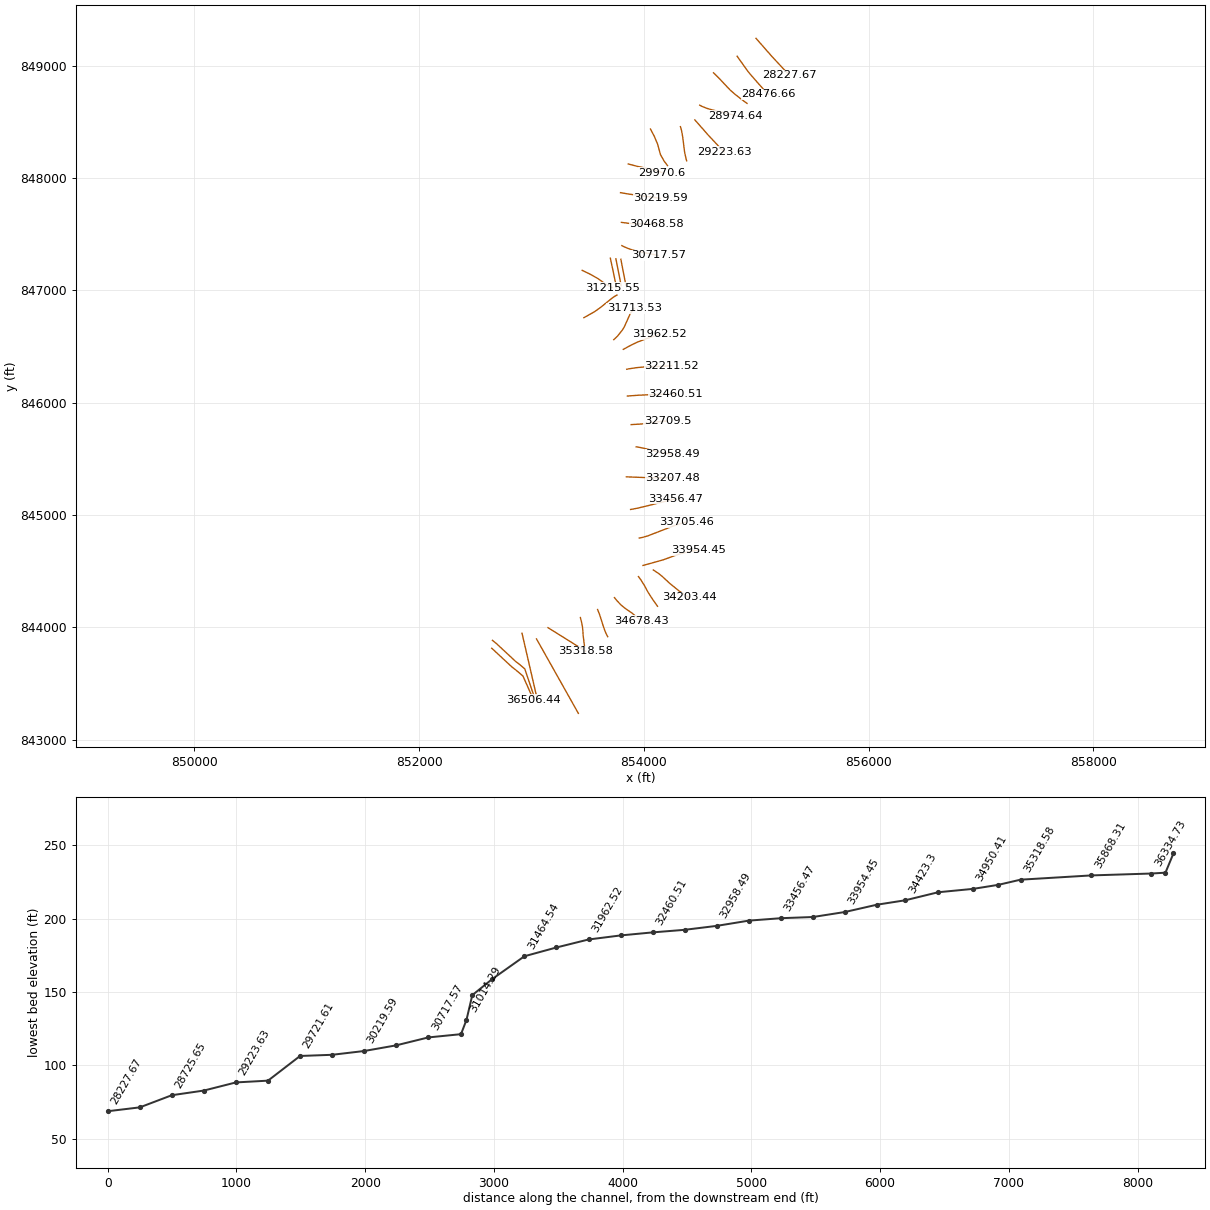
HEC-RAS study 18726_ras.prj: 18726

--- 18726_ras.g01 (geometry) --- (continued)

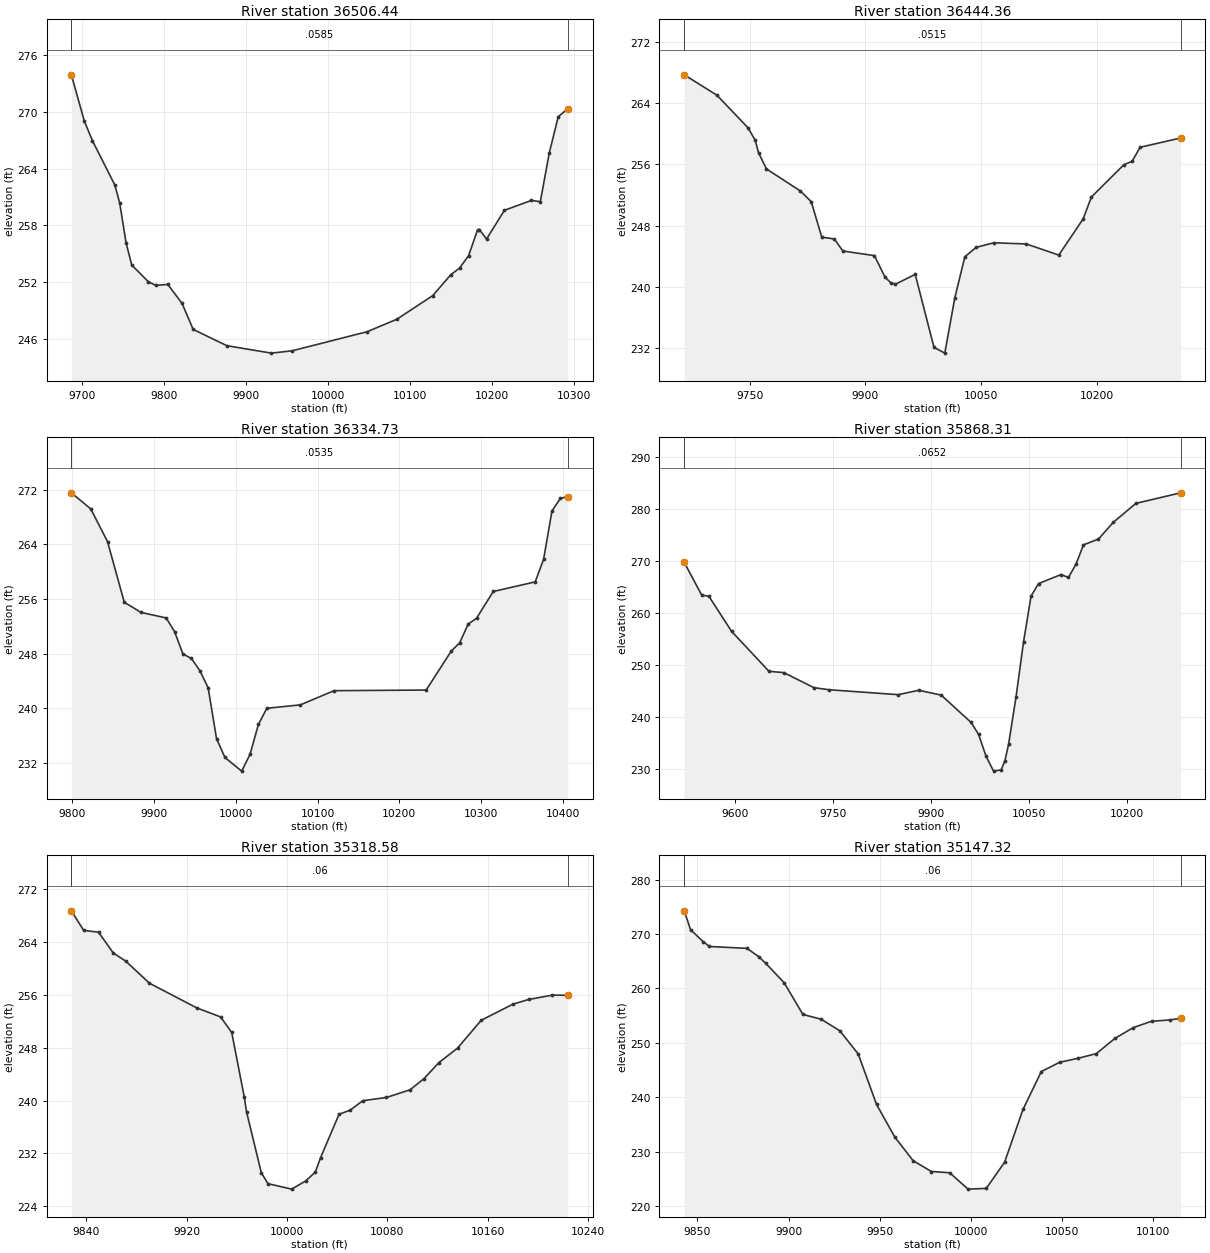
Type RM Length L Ch R = 1 ,36506.44,62.083300,62.083300,62.083300
XS GIS Cut Line= 6
852645.933556688843814.917458564 852657.72335608843804.434243281
852822.661469255843650.954616744852859.755503375843622.003798057
852924.059555349 843567.59690356853018.759139603843354.458647541
#Sta/Elev= 30
9686.838 273.9059702.615269.03539712.554266.95019739.874262.26989745.823260.3744
9753.534256.18929760.502253.82179780.853252.04659789.861251.67369804.541251.7688
9821.832249.77269835.492247.01879876.471245.30339930.882244.51569956.253244.7616
10047.74246.777710083.93248.0919 10127.7250.586310149.59252.777110160.53253.5031
10171.47254.805110182.41257.525310184.66257.566710193.36256.559910215.24259.6005
10248.07260.640210259.01260.510910269.95 265.666 10280.9269.482410292.43270.3125
#Mann= 3 , 0 , 0
9686.838  0.0585       09686.838  0.0585       010292.43  0.0585       0
#XS Ineff= 2 , 0
       0                10088.56       0
Bank Sta=9686.838,10292.43
Exp/Cntr=0.3,0.1

Type RM Length L Ch R = 1 ,36444.36,109.628100,109.628100,109.628100
XS GIS Cut Line= 6
 852652.40791945843885.408726049852692.190837119843852.465244073
852857.128909489843698.985821877852894.222931396843670.035044929
852940.012440453843631.931411201853023.333180279843385.308816257
#Sta/Elev= 30
9665.162267.69229707.478265.04089747.971260.77069757.132259.16669761.631257.5035
9771.812255.4134 9815.85252.52849829.929251.13119843.589246.50719859.889246.2694
9870.909244.69849911.888244.09269925.548241.30029933.287 240.5349939.207240.3669
9964.785 241.648 9989.17232.111310003.19 231.368 10016.2238.603510029.21243.9512
10043.94245.174410066.61245.769110108.83245.619110151.05 244.16710182.72248.9002
10193.27251.7349 10235.5255.960710246.05 256.39810256.61258.237710309.06 259.447
#Mann= 3 , 0 , 0
9665.162  0.0515       09665.162  0.0515       010309.06  0.0515       0
#XS Ineff= 2 , 0
       0                10149.16       0
Bank Sta=9665.162,10309.06
Exp/Cntr=0.3,0.1

Type RM Length L Ch R = 1 ,36334.73,466.422900,466.422900,466.422900
XS GIS Cut Line= 2
852915.624463247843948.096070007853052.214986465843356.222163784
#Sta/Elev= 30
9798.664271.54389822.368269.19429842.893264.40519863.419255.51799883.945254.0364
9914.733253.22329924.996251.21069935.259247.93099945.522247.29819955.784245.5275
9966.047243.0056 9976.31235.56379986.573232.7939 10007.1230.792810017.36233.2666
10027.62237.645110037.89239.996210078.94 240.49510119.99242.572610232.88242.6652
10263.67248.391810273.93249.5899 10284.2252.317910294.46253.170210314.98257.0972
 10366.3258.503610376.56261.801110386.82268.899610397.09270.726510406.09 270.993
#Mann= 3 , 0 , 0
9798.664  0.0535       09798.664  0.0535       010406.09  0.0535       0
#XS Ineff= 2 , 0
       0                10244.97       0
Bank Sta=9798.664,10406.09
Exp/Cntr=0.3,0.1

Type RM Length L Ch R = 1 ,35868.31,549.727900,549.727900,549.727900
XS GIS Cut Line= 2
853044.353361073843898.113141902853416.991561817843235.306425856
#Sta/Elev= 30
 9522.18269.76729548.696263.51029560.168  263.199594.584256.48539651.945248.7579
9674.889248.49779720.777245.60389743.721245.20289849.983244.25029881.386245.0952
9915.802244.1667 9961.69238.88889973.162236.57619984.635232.32619996.107229.5012
10007.58229.736710013.23231.383410019.05 234.68410030.52243.856910041.99 254.449
10053.47263.263410064.94265.679210099.36267.413310110.83266.8607 10122.3269.4112
10133.77273.141810156.72274.268410179.66 277.51810214.08281.145910282.56283.1828
#Mann= 3 , 0 , 0
 9522.18  0.0652       0 9522.18  0.0652       010282.56  0.0652       0
#XS Ineff= 2 , 0
       0                               0
Bank Sta=9522.18,10282.56
Exp/Cntr=0.3,0.1

Type RM Length L Ch R = 1 ,35318.58,171.261700,171.261700,171.261700
XS GIS Cut Line= 2
853146.655573859843997.965388535853482.032918801843788.484363393
#Sta/Elev= 30
9828.238268.72119838.077265.75519849.867265.48629861.658262.33459871.589261.1024
9890.465257.75989928.218254.01929947.094252.66239955.981250.31679965.971240.5331
9967.772238.30479979.562229.06959984.847227.417910003.72226.590110014.93227.8308
 10022.6229.169910026.72 231.32710041.48237.9242 10050.3  238.5410060.35239.9737
10079.23240.464610098.11241.630510109.26243.337610121.05245.749910135.86247.9324
10154.73252.1502   10180254.589310192.49255.299410211.36255.960810223.66255.9396
#Mann= 3 , 0 , 0
9828.238    0.06       09828.238    0.06       010223.66    0.06       0
#XS Ineff= 2 , 0
       0                               0
Bank Sta=9828.238,10223.66
Exp/Cntr=0.3,0.1

Type RM Length L Ch R = 1 ,35147.32,196.903200,196.903200,196.903200
XS GIS Cut Line= 6
853434.872483444844088.309558697853447.484070295844038.388495807
 853453.77699719844002.735771644  853457.4211536843968.142950986
853459.015141594843932.922302299853473.283510016843819.177918149
#Sta/Elev= 30
9842.753274.26259846.211 270.7999853.166268.58649856.605 267.7069877.173267.3643
9883.614265.84579887.457264.62539897.697  260.999907.852255.21459918.006254.3153
9928.161 252.2029938.239247.93939948.294238.6547 9958.35232.64069968.391228.3152
9978.401226.33529988.412226.10419998.501223.094410008.49223.233410018.56228.0356
10028.64237.740210038.72 244.715 10048.8246.418310058.88247.149510068.96248.0191
10079.03250.790410089.11252.788810099.19253.954710109.27254.203610115.14254.4877
#Mann= 3 , 0 , 0
9842.753    0.06       09842.753    0.06       010115.14    0.06       0
#XS Ineff= 2 , 0
       0                               0
Bank Sta=9842.753,10115.14
Exp/Cntr=0.3,0.1

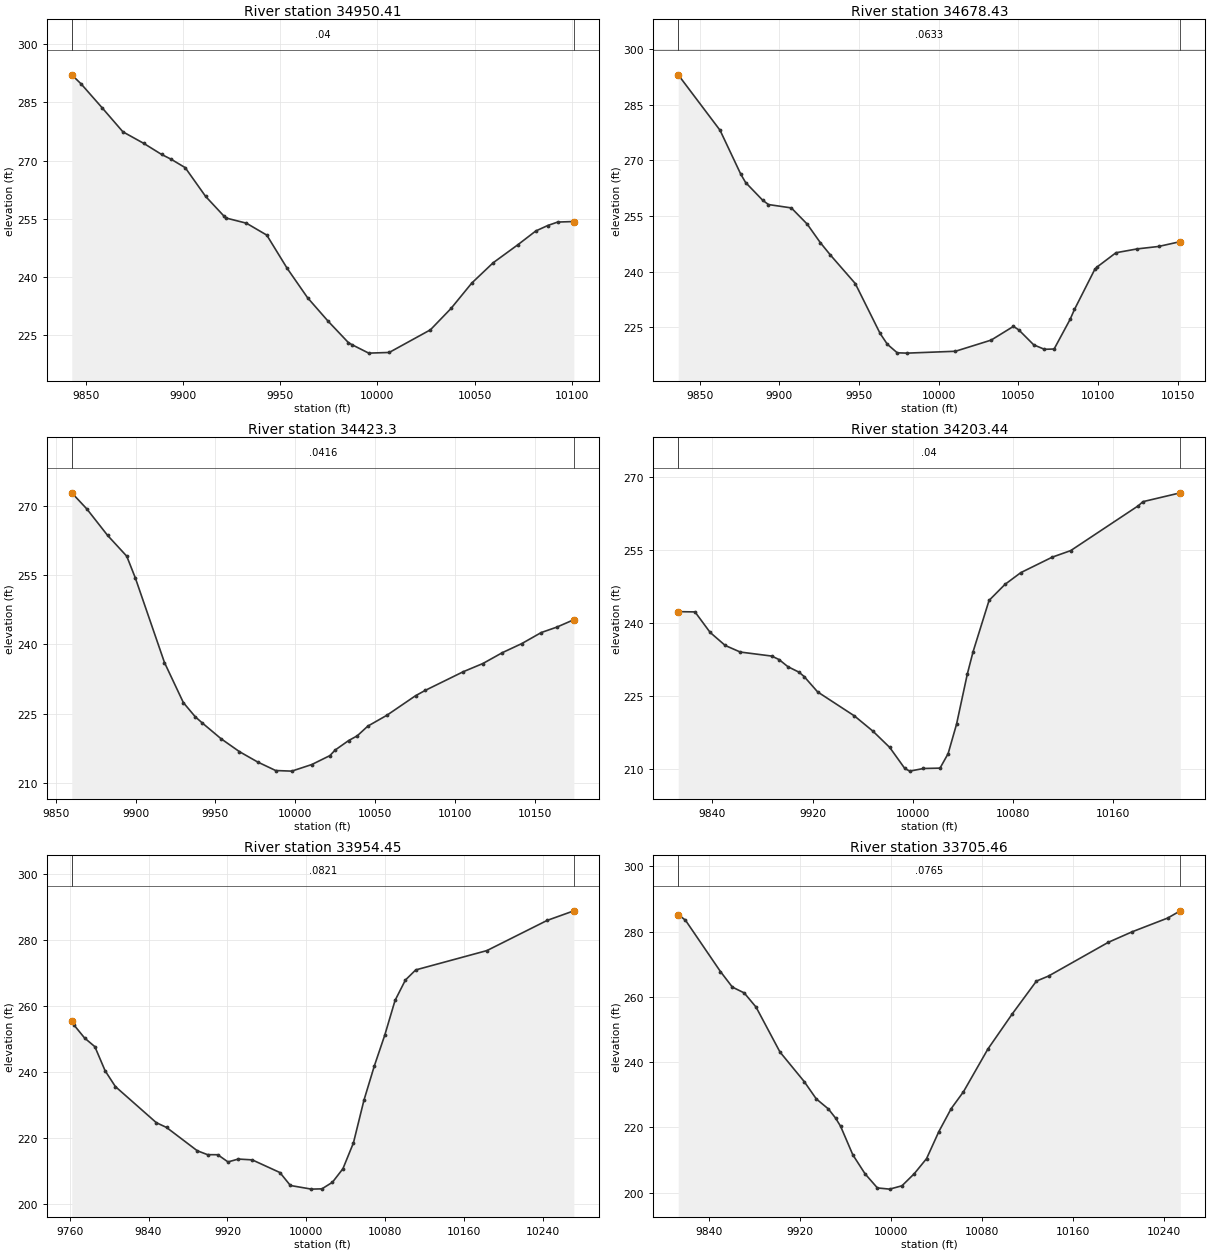
Type RM Length L Ch R = 1 ,34950.41,271.987500,271.987500,271.987500
XS GIS Cut Line= 6
853588.143040983844159.502586653853606.806265812844111.883016096
 853638.64962339844011.718118256 853653.99096505843967.749943729
853671.399877484843929.390085608853678.111681647843917.789399612
#Sta/Elev= 29
9842.749292.13459847.585289.77839858.326283.65669869.066277.42729879.807274.4432
9888.945 271.5979893.895270.34929901.118268.18439911.611260.7736 9920.94255.7501
9922.104  255.199932.597 253.856 9943.09250.77939953.584242.20549964.077234.6227
 9974.57228.61229985.063223.05319986.954222.49859995.556220.3255 10006.1220.4992
10027.29226.340610037.89231.846410048.59238.411510059.57243.637810072.21248.2595
10081.53 251.84710087.69253.256310092.77254.1445 10101.1254.2808
#Mann= 3 , 0 , 0
9842.749    0.04       09842.749    0.04       0 10101.1    0.04       0
#XS Ineff= 2 , 0
       0                               0
Bank Sta=9842.749,10101.1
Exp/Cntr=0.3,0.1

Type RM Length L Ch R = 1 ,34678.43,255.129900,255.129900,255.129900
XS GIS Cut Line= 6
853737.973608109844265.229312596853764.054005809844233.694485427
853797.640875819844199.126106426853829.901387267844172.056237988
853895.140407359844126.973370223853975.199635836844059.799008066
#Sta/Elev= 30
9836.493 293.0759862.745278.11369875.721 266.2979878.773264.03519889.538259.2321
9893.123258.09079907.474257.18089917.424 252.8179925.614247.84489932.033244.4549
 9947.59 236.7899963.147223.35649967.727220.40649973.938218.1067 9980.08218.0179
10010.44  218.5210032.87 221.53110046.86225.2333 10050.2224.288110059.61220.2443
10066.29219.053410072.38219.126410082.39227.100710085.14229.7844 10097.9240.6001
10099.42241.2708 10111.2245.094210124.57246.130410137.94246.783610151.58 248.089
#Mann= 3 , 0 , 0
9836.493  0.0633       09836.493  0.0633       010151.58  0.0633       0
#XS Ineff= 2 , 0
       0                               0
Bank Sta=9836.493,10151.58
Exp/Cntr=0.3,0.1

Type RM Length L Ch R = 1 , 34423.3,219.854500,219.854500,219.854500
XS GIS Cut Line= 6
853951.562677865 844452.58842332853971.732322715844425.661987927
854005.814649801 844371.53114696854037.410251875844312.125175608
854078.862440386 844248.81543124854121.094627813844188.277305988
#Sta/Elev= 30
 9860.07272.84379869.551269.33429882.483263.62459894.495 259.1149899.846254.4228
9918.129236.06199929.946227.38799937.382224.32179941.763222.9856 9953.58 219.553
9965.081216.75899976.413214.52919987.746212.67049997.815212.541210010.37213.9709
10021.71215.905410024.97217.105110033.48219.175910038.82 220.18910045.44 222.292
10057.39224.646310075.33228.8791 10081.3230.017310105.29234.093110117.49 235.857
10129.68  238.2110141.87240.180210154.06242.5714 10163.8243.746910174.45245.3517
#Mann= 3 , 0 , 0
 9860.07  0.0416       0 9860.07  0.0416       010174.45  0.0416       0
#XS Ineff= 2 , 0
       0                               0
Bank Sta=9860.07,10174.45
Exp/Cntr=0.3,0.1

Type RM Length L Ch R = 1 ,34203.44,248.990700,248.990700,248.990700
XS GIS Cut Line= 6
854083.897624793844511.413436212854132.872181559844478.493539629
854164.182414229844453.110164155854229.337855047 844392.67832093
 854311.58643453844325.686133146  854400.4453947 844267.50484066
#Sta/Elev= 30
9812.815242.32459826.192242.26949838.242238.05969850.291235.3722 9862.34234.0167
9887.438233.18959893.252232.47069900.311231.00889909.131229.88479913.249228.9862
9924.036225.81999953.393 220.8839968.071217.76759981.553214.40049993.524 210.093
 9997.51209.535810008.47210.078410021.66210.151810028.11 213.12310034.85219.1917
10043.45229.508610048.04234.091110060.79244.636210073.45247.920110086.11250.3449
10111.26253.535510125.92254.872410179.97264.113910183.49264.931710213.36266.7518
#Mann= 3 , 0 , 0
9812.815    0.04       09812.815    0.04       010213.36    0.04       0
#XS Ineff= 2 , 0
       0                               0
Bank Sta=9812.815,10213.36
Exp/Cntr=0.3,0.1

Type RM Length L Ch R = 1 ,33954.45,248.990600,248.990600,248.990600
XS GIS Cut Line= 6
853992.446347385844551.679883412854168.643720533 844600.49358829
854280.334690931 844641.22374363854338.839646279844659.389735666
854415.438900197844677.089450476 854481.72534713844687.486514487
#Sta/Elev= 30
9762.228255.54359764.878254.15479775.255250.35079785.631247.73539796.008240.4366
9806.385235.64959847.891 224.6949858.268 223.2439889.398216.17789899.775214.9964
9910.151214.97269920.528212.79139930.904213.66079945.062213.41499973.096209.5768
9983.733205.646410005.01204.544710015.66204.629210026.31  206.6210036.96 210.736
10047.61218.567810058.27231.515310068.83 241.946 10079.3251.183410089.78261.7606
10100.25267.935610110.72271.008310182.85276.866610243.87286.015510270.92288.9216
#Mann= 3 , 0 , 0
9762.228  0.0821       09762.228  0.0821       010270.92  0.0821       0
#XS Ineff= 2 , 0
       0  9940.5                       0
Bank Sta=9762.228,10270.92
Exp/Cntr=0.3,0.1

Type RM Length L Ch R = 1 ,33705.46,248.990700,248.990700,248.990700
XS GIS Cut Line= 6
853958.784278045844794.946208681853990.378708808844801.791504964
854037.167390811844815.573095605854263.807131188844903.470707621
854336.505808393844927.051938346854375.760970035844937.489571995
#Sta/Elev= 30
9812.789285.21689819.149283.47399849.934267.73799860.359262.99749870.784261.2087
9881.208256.85669902.219243.10989923.481234.07569934.112228.75859944.743225.6821
9951.021222.90529955.456220.39439966.249211.61949977.041205.78839987.834201.4871
9998.626201.120610009.44202.148710020.25 205.85410031.06210.475510041.87 218.762
10052.68225.7736 10063.5230.952810084.89243.991910106.25254.728310127.61264.8367
10138.27266.384810190.84276.720710211.86279.946310242.93284.135110254.07286.3533
#Mann= 3 , 0 , 0
9812.789  0.0765       09812.789  0.0765       010254.07  0.0765       0
#XS Ineff= 2 , 0
       0                               0
Bank Sta=9812.789,10254.07
Exp/Cntr=0.3,0.1

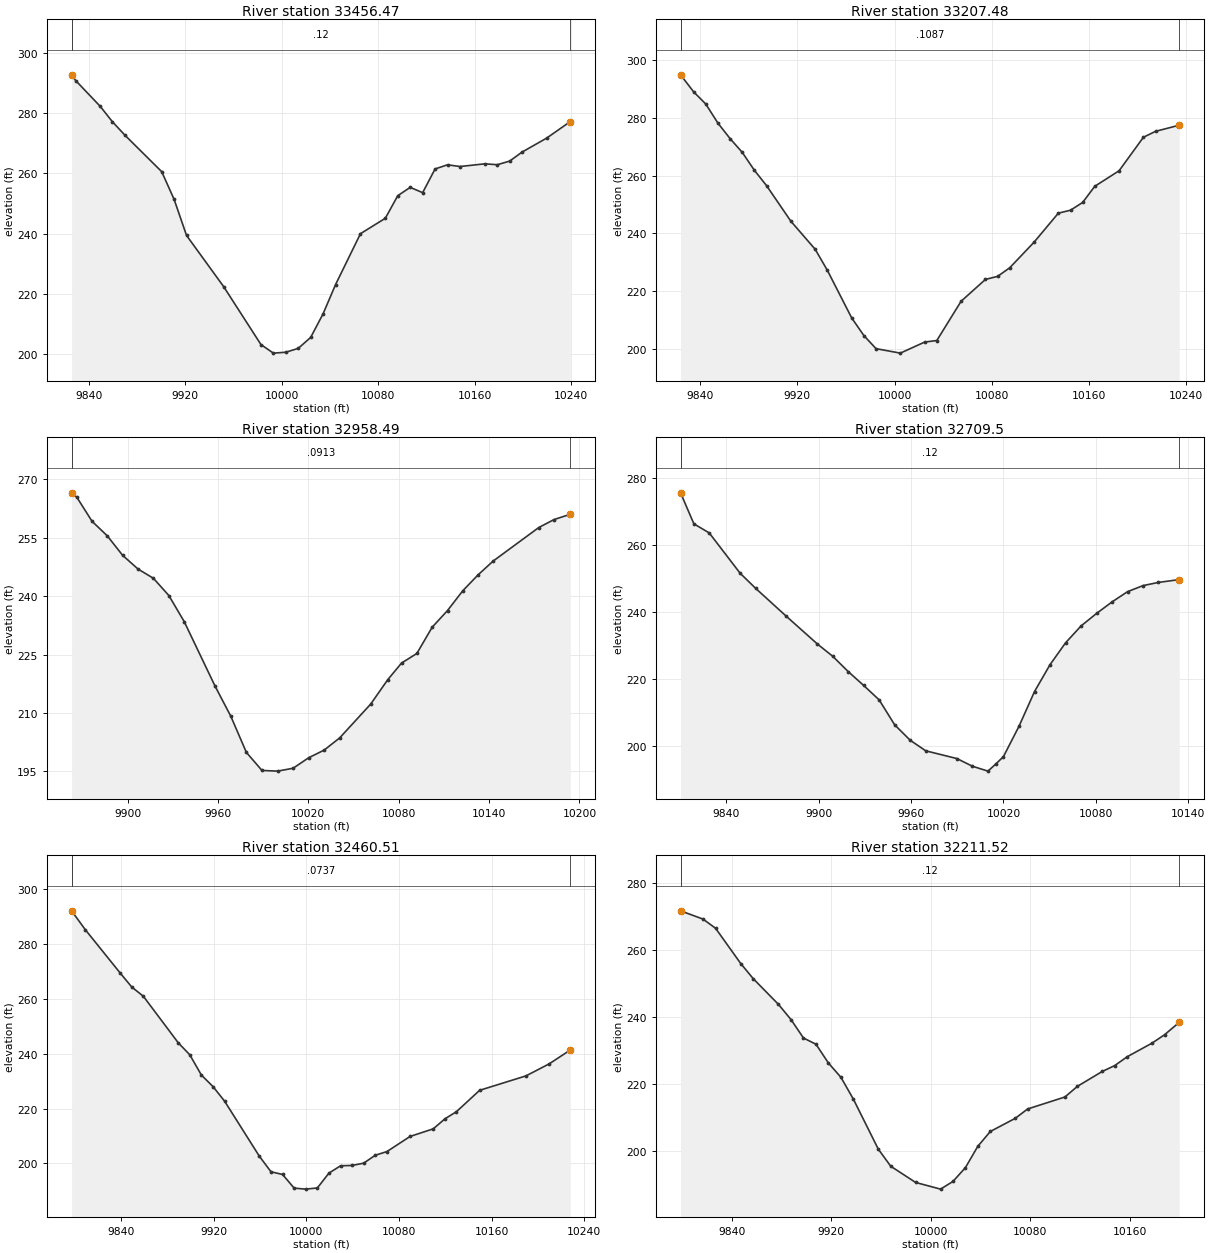
Type RM Length L Ch R = 1 ,33456.47,248.990600,248.990600,248.990600
XS GIS Cut Line= 6
853881.671488545845049.705650839 853885.42282778845050.243943834
853948.441094565845062.339249848854050.600243936845087.059965654
854232.310212408845133.032150821854284.224965044845143.606180764
#Sta/Elev= 30
9825.934292.74459829.297 290.8529849.658 282.2779859.841277.13059870.023272.7421
9900.641260.58429910.929251.38049921.218239.40949952.084 222.358 9982.95203.1475
9993.238200.310510003.54200.603910013.85 201.89310024.17205.531610034.48213.3876
 10044.8223.077110065.43239.975110086.06245.103410096.37 252.59810106.69255.3656
   10117253.607910127.32261.481810137.63 262.86210147.95262.291710168.58263.1842
10178.89262.888210189.18264.096310199.39267.0715 10219.8271.719210239.42277.2216
#Mann= 3 , 0 , 0
9825.934    0.12       09825.934    0.12       010239.42    0.12       0
#XS Ineff= 2 , 0
       0                               0
Bank Sta=9825.934,10239.42
Exp/Cntr=0.3,0.1

Type RM Length L Ch R = 1 ,33207.48,248.990600,248.990600,248.990600
XS GIS Cut Line= 6
853844.252738724845340.022752941854019.279955874845333.444952219
854021.278603433845333.371413901854030.974518287845333.036033445
854136.882711493845331.281387934854254.480079093845333.297425873
#Sta/Elev= 30
9823.849294.83829834.604288.96339844.611284.74489854.618278.13779864.625272.7861
9874.632268.03559884.639261.82439894.646256.52599914.661244.22389934.675234.5249
9944.682227.25339964.696210.81049974.703204.7267 9984.71200.199910004.72198.6532
10024.73202.472810034.73203.013110054.73216.585710074.74224.125910084.74225.1778
10094.74228.155510114.74236.984310134.74247.025410144.75248.044310154.75250.7306
10164.75256.319310184.75  261.6910204.75273.257710214.76275.310110234.24 277.429
#Mann= 3 , 0 , 0
9823.849  0.1087       09823.849  0.1087       010234.24  0.1087       0
#XS Ineff= 2 , 0
       0                               0
Bank Sta=9823.849,10234.24
Exp/Cntr=0.3,0.1

Type RM Length L Ch R = 1 ,32958.49,248.990700,248.990700,248.990700
XS GIS Cut Line= 6
853931.583098122845607.102276308853962.317169756845602.164954927
854017.114192534845590.279218965854136.040896718845559.633811522
854190.447101836845549.688107853854255.783660696845541.649931893
#Sta/Elev= 30
9862.766266.48179866.227265.35059876.355259.17359886.483255.43379896.639250.4539
9906.872 246.9279917.105244.55279927.337240.1378 9937.57233.42729958.128216.8112
9968.479209.1672 9978.83199.88699989.181195.25429999.534195.079210009.85 195.815
10020.16198.501210030.47200.473910040.78203.5984 10061.4212.290410072.78218.5753
10081.89222.810110092.05225.270310102.22232.008510112.39236.278410122.55241.3609
10132.68245.428910142.76248.989310173.01257.580710183.09 259.61510193.93260.9842
#Mann= 3 , 0 , 0
9862.766  0.0913       09862.766  0.0913       010193.93  0.0913       0
#XS Ineff= 2 , 0
       0                               0
Bank Sta=9862.766,10193.93
Exp/Cntr=0.3,0.1

Type RM Length L Ch R = 1 , 32709.5,248.990600,248.990600,248.990600
XS GIS Cut Line= 6
853886.354099963845804.820223371853969.913812318845809.735728039
 854025.66699548 845815.72233763854076.161268602845823.135400532
854162.082129404845834.467192227854208.540558991 845837.51044935
#Sta/Elev= 30
 9810.18275.62649818.832266.35879828.838 263.622 9848.88 251.5829858.902  247.09
9878.945238.68589899.006230.44359909.064226.73819919.121222.16179929.179 218.012
9939.236213.69239949.294206.24599959.397201.61939969.504198.46129989.717196.1525
9999.825193.852610009.92192.388310015.26194.6189   10020196.745110030.09205.8019
10040.18216.190510050.26 224.23210060.35230.760510070.43 235.81710080.52239.5648
10090.59243.010710100.61246.060310110.63247.869310120.65248.827210134.22249.6719
#Mann= 3 , 0 , 0
 9810.18    0.12       0 9810.18    0.12       010134.22    0.12       0
#XS Ineff= 2 , 0
       0                               0
Bank Sta=9810.18,10134.22
Exp/Cntr=0.3,0.1

Type RM Length L Ch R = 1 ,32460.51,248.990600,248.990600,248.990600
XS GIS Cut Line= 6
853853.245225302846058.943086263 853868.50862109846060.388759956
853958.941997665846066.740752719854054.408257361846070.905555975
854056.407162059846070.971737862 854283.22470288846078.470339638
#Sta/Elev= 30
9797.455292.03019809.262285.16919839.343269.40089849.368264.27639859.393260.9056
9889.467243.97839899.491239.56689909.507232.18479919.516228.00019929.526222.6798
9959.554202.60649969.564196.95879979.573195.97389989.583190.99549999.592190.6325
 10009.6 191.063 10019.6196.464410029.61199.137810039.61199.261810049.62200.0931
10059.62202.988510069.63 204.30710089.64 209.82710109.65212.595410119.66216.2273
10129.66218.846310149.67226.6316 10189.7231.894210209.71236.268310227.94241.3172
#Mann= 3 , 0 , 0
9797.455  0.0737       09797.455  0.0737       010227.94  0.0737       0
#XS Ineff= 2 , 0
       0                               0
Bank Sta=9797.455,10227.94
Exp/Cntr=0.3,0.1

Type RM Length L Ch R = 1 ,32211.52,248.990700,248.990700,248.990700
XS GIS Cut Line= 6
 853847.31030944846297.522426775853861.160188059846300.421495297
853930.893262889846311.327608955854001.635090677846317.779599298
 854184.81233337846325.334692373854246.823901515846329.064795942
#Sta/Elev= 30
9798.656271.63119816.692269.17249826.814266.43029847.057255.90539857.179251.3541
9877.422243.70599887.511239.16929897.552233.66179907.594231.81319917.635226.1939
9927.677221.93939937.718215.3977 9957.79200.4633  9967.8195.3755 9987.82 190.544
10007.84188.556310017.85190.863710027.85194.979410037.86 201.36510047.87205.7592
10067.89209.681810077.89212.481910107.92216.059910117.93 219.23810137.94223.6818
10147.96225.432210157.98228.066210178.02232.146110188.03234.633810199.88238.3402
#Mann= 3 , 0 , 0
9798.656    0.12       09798.656    0.12       010199.88    0.12       0
#XS Ineff= 2 , 0
       0                               0
Bank Sta=9798.656,10199.88
Exp/Cntr=0.3,0.1

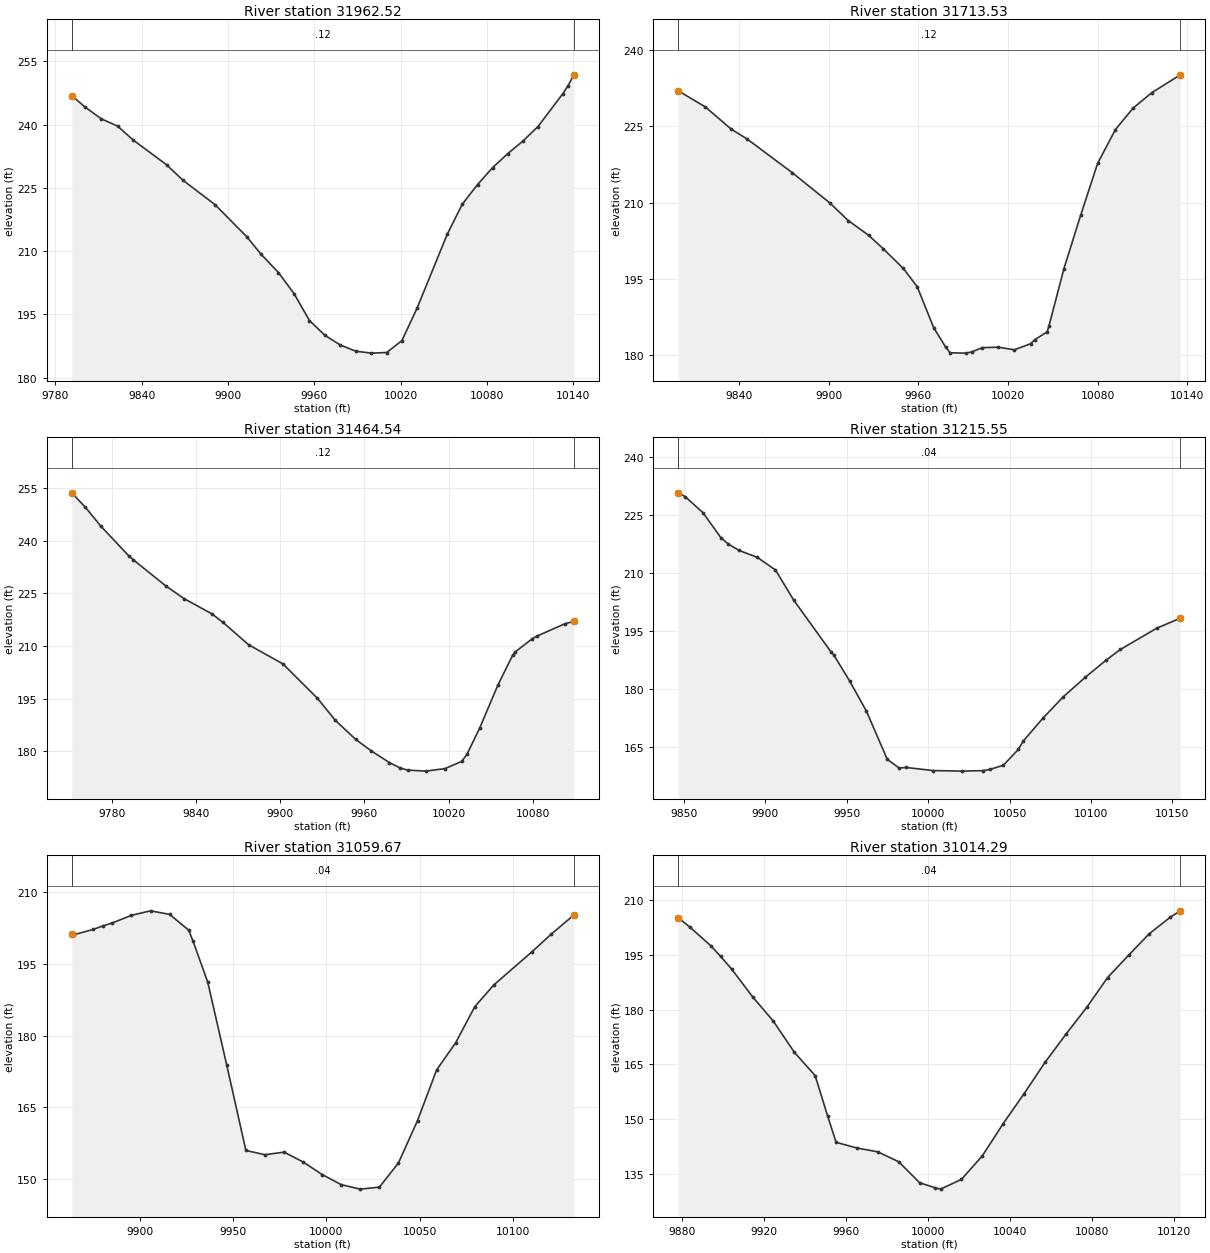
Type RM Length L Ch R = 1 ,31962.52,248.990600,248.990600,248.990600
XS GIS Cut Line= 6
853816.959148628846474.633931322853887.753925165846512.858332157
853937.657508885 846536.88356172854017.240324352846568.190269788
854121.940700556846602.327958084 854138.90686614846607.062911748
#Sta/Elev= 30
9791.375246.87749800.513244.18439811.878241.37639823.243239.63939834.242236.2948
9857.336230.45649868.701226.79059890.971221.01879913.168213.36339922.874 209.294
9935.118204.8903 9945.88199.92929956.642193.51849967.404190.01579978.166187.6997
9988.928186.23729999.687185.786710010.35185.9332 10020.9188.753110031.42196.4107
10052.45213.987610062.97221.151310073.49225.760510084.01 229.80110094.53233.1132
10105.05236.091310115.56 239.543 10132.8247.328210136.42249.223310140.48251.8053
#Mann= 3 , 0 , 0
9791.375    0.12       09791.375    0.12       010140.48    0.12       0
#XS Ineff= 2 , 0
       0                               0
Bank Sta=9791.375,10140.48
Exp/Cntr=0.3,0.1

Type RM Length L Ch R = 1 ,31713.53,248.990700,248.990700,248.990700
XS GIS Cut Line= 6
853731.975051298846560.531386874853765.278674379846592.153059944
853811.663338918846650.699502284853826.612296725846676.626719138
853879.876210086846795.055091491853912.709155346846839.400521721
#Sta/Elev= 30
9799.337232.02369817.298228.88219834.873224.45839845.261222.56489875.589215.9035
9900.749209.94029913.039206.47169926.724203.56319936.551200.89959949.972197.0228
9959.222193.4344 9970.27185.34719978.205181.56859981.232180.41659991.979180.3463
9995.648180.586210002.72181.424210013.49181.515510024.27181.002410035.05182.1957
10037.83182.979810046.17184.539610047.35185.6661 10057.4197.004810068.64207.5604
10079.94217.728510091.81224.376410103.74228.645810116.26231.668610135.26235.1727
#Mann= 3 , 0 , 0
9799.337    0.12       09799.337    0.12       010135.26    0.12       0
#XS Ineff= 2 , 0
       0                               0
Bank Sta=9799.337,10135.26
Exp/Cntr=0.3,0.1

Type RM Length L Ch R = 1 ,31464.54,248.990600,248.990600,248.990600
XS GIS Cut Line= 6
853466.156745819846756.244506485853560.129783255846809.038723911
853614.848731931846847.663688082853714.759218486846928.745101366
 853741.68409313846947.676152591853760.723932793846957.571738995
#Sta/Elev= 30
9751.432253.67959761.212249.52149772.271244.13699791.896  235.79 9795.41234.5631
9818.584227.10729831.493223.52259851.291219.19149859.287 216.7369877.489210.3788
 9901.97 204.922 9926.46195.15249939.323188.82959953.828183.39919965.049180.1002
9977.912176.77479985.625175.23429990.775174.654310003.61174.356510017.39175.0699
10029.43177.1288 10033.2179.205610042.34186.758210055.23198.918710065.81207.4673
10067.46208.323210079.68212.0825 10083.2212.873510103.02216.376710109.33217.0444
#Mann= 3 , 0 , 0
9751.432    0.12       09751.432    0.12       010109.33    0.12       0
#XS Ineff= 2 , 0
       0                               0
Bank Sta=9751.432,10109.33
Exp/Cntr=0.3,0.1

Type RM Length L Ch R = 1 ,31215.55,155.879800,155.879800,155.879800
XS GIS Cut Line= 6
853451.039061502847177.520951584853521.714764538847143.517876543
 853591.47468239847103.986281155853666.132079382847051.245227683
853693.797062353 847035.93109166853718.047335452847024.742011346
#Sta/Elev= 30
9846.445230.64979850.767229.65649861.678225.50429872.589219.11549877.196217.4312
9883.783215.79639894.983214.01189906.182210.75949917.382 202.9779940.229 189.658
9941.985188.84699951.766 182.084 9962.04174.35239974.838161.92039982.095159.6705
9986.375159.814710002.86159.020310020.69158.869510033.91159.000110038.02159.3195
10046.16160.391610055.35164.4702 10058.4166.636210070.65172.614410082.89178.0114
10096.52183.087810109.41187.547410118.08190.261910140.48195.759710154.85198.3197
#Mann= 3 , 0 , 0
9846.445    0.04       09846.445    0.04       010154.85    0.04       0
#XS Ineff= 2 , 0
       0                               0
Bank Sta=9846.445,10154.85
Exp/Cntr=0.3,0.1

Type RM Length L Ch R = 1 ,31059.67,45.380300,45.380300,45.380300
XS GIS Cut Line= 2
853701.573442262847286.305040809853757.116183348847023.030502545
#Sta/Elev= 29
9863.572201.21939864.905201.16419875.125202.24239880.171202.97299885.346203.6085
9895.566205.19699905.786206.13929916.006205.39349926.226202.09369928.615199.7335
9936.446191.19579946.666173.74759956.886155.93779967.106155.04159977.327155.5856
9987.547153.53019997.767150.893210007.99148.774910018.21147.836410028.43148.2568
10038.65153.324910048.87162.210610059.09172.800210069.31178.506910079.53186.0463
10089.75 190.61810110.19197.555510120.41201.208510132.64205.2662
#Mann= 3 , 0 , 0
9863.572    0.04       09863.572    0.04       010132.64    0.04       0
#XS Ineff= 2 , 0
       0                               0
Bank Sta=9863.572,10132.64
Exp/Cntr=0.3,0.1

Type RM Length L Ch R = 1 ,31014.29,42.435800,42.435800,42.435800
XS GIS Cut Line= 2
853751.040230822 847280.56088838853797.940692624847040.196472676
#Sta/Elev= 29
9878.073205.10499883.738202.52989893.927197.46199898.749194.52149904.116191.0629
9914.304183.51289924.493176.81249934.681 168.353 9944.87161.93829950.966150.8773
9955.058143.72159965.247142.16619975.436141.11429985.624138.40699995.813132.6828
10003.18131.3279   10006130.929110016.19133.583310026.38140.009810036.57148.8328
10046.76157.011910056.94165.533910067.13173.224210077.32180.594210087.51188.7528
 10097.7194.816110107.89200.754310118.08205.237110122.97206.9768
#Mann= 3 , 0 , 0
9878.073    0.04       09878.073    0.04       010122.97    0.04       0
#XS Ineff= 2 , 0
       0                               0
Bank Sta=9878.073,10122.97
Exp/Cntr=0.3,0.1

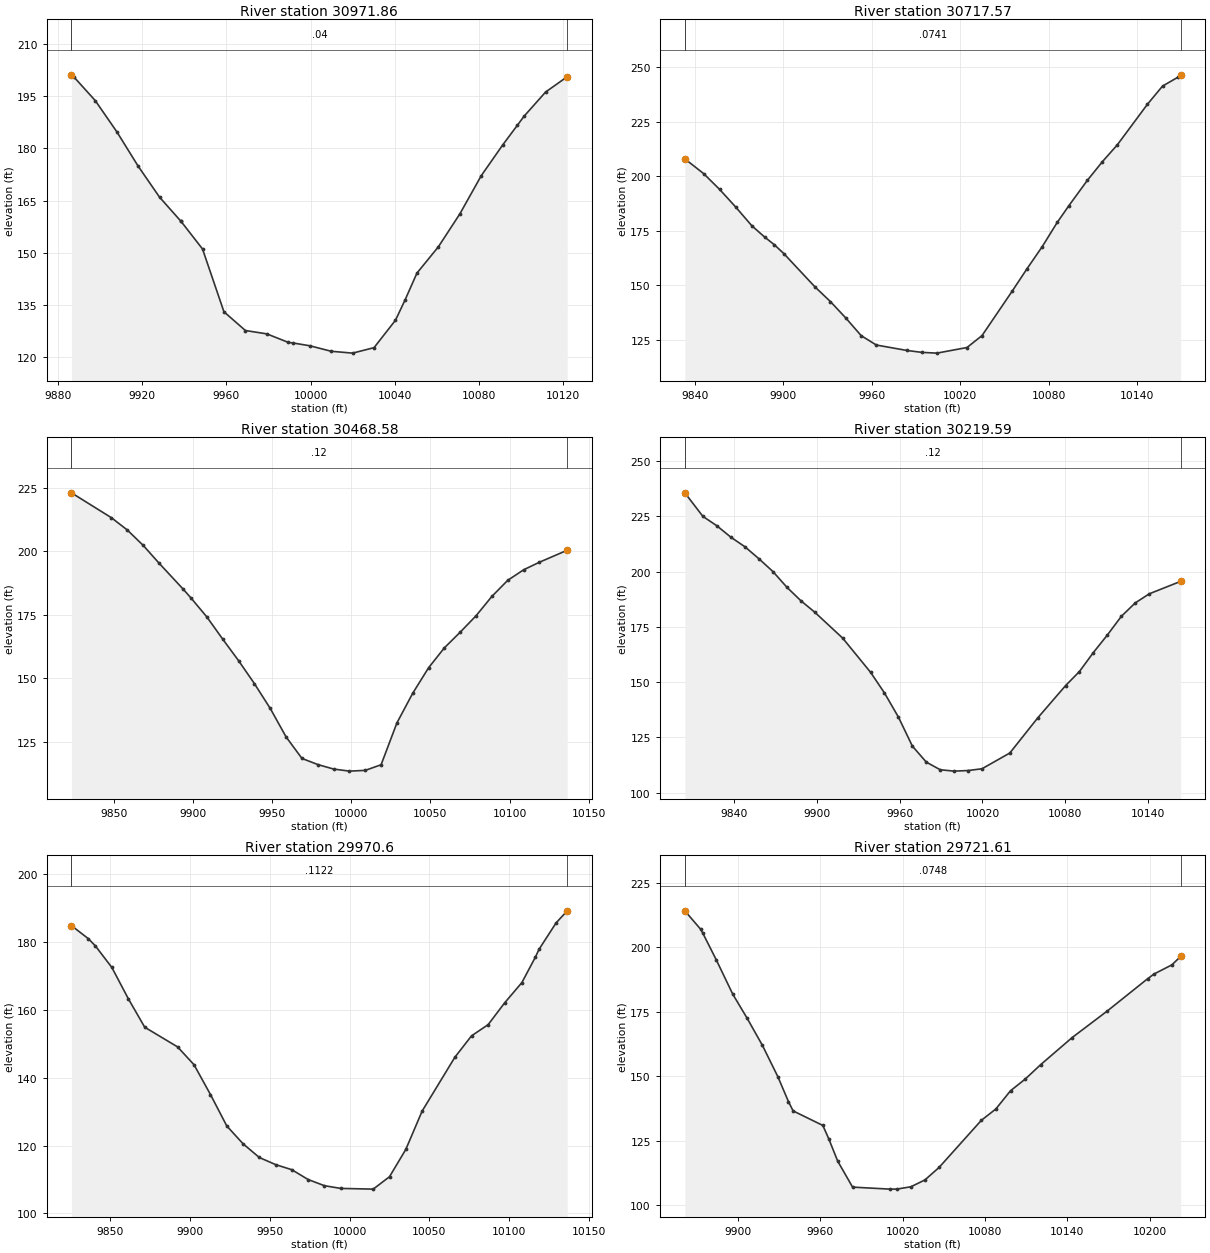
Type RM Length L Ch R = 1 ,30971.86,254.285400,254.285400,254.285400
XS GIS Cut Line= 2
853795.228448295847276.111025136853839.463257987847044.913125681
#Sta/Elev= 30
9886.451  201.099887.582200.50129897.763193.68329907.945184.78359918.126174.8647
9928.307165.94659938.449159.04219938.489159.0156 9948.67151.10299958.851133.0671
9969.033127.69179979.214126.72429989.396124.28419991.663124.10979999.577123.3146
10009.76121.734310019.94121.198610030.12122.7726 10040.3 130.65110044.88136.5141
10050.48144.168610060.67151.733210070.85161.163410081.03172.153810091.21180.9702
10098.09186.551710101.39189.238110111.57196.151210121.75200.513910121.84200.5485
#Mann= 3 , 0 , 0
9886.451    0.04       09886.451    0.04       010121.84    0.04       0
#XS Ineff= 2 , 0
       0                               0
Bank Sta=9886.451,10121.84
Exp/Cntr=0.3,0.1

Type RM Length L Ch R = 1 ,30717.57,248.990600,248.990600,248.990600
XS GIS Cut Line= 6
853803.834122952847397.731535418853814.362395173847392.031241778
853858.986923955847372.351041355853902.320895419847357.632172079
853953.491503102847345.047512238854127.042944401847310.030593147
#Sta/Elev= 30
9833.169207.94819845.838201.23759856.767193.95899867.697185.85629878.626177.2896
9887.348172.10139893.913168.59459900.263164.58579921.385149.33179931.947142.5564
9942.437134.98899952.735126.99719963.033122.68499983.629120.21149993.914119.3189
10004.12118.972910024.52121.544510034.72127.007210055.13147.311210065.33157.7129
10075.53167.723710085.73178.843510093.68186.545110106.13198.078210116.33206.6267
10126.53 214.40910146.94232.979110157.14241.266510167.34245.247210169.42 246.434
#Mann= 3 , 0 , 0
9833.169  0.0741       09833.169  0.0741       010169.42  0.0741       0
#XS Ineff= 2 , 0
       0                               0
Bank Sta=9833.169,10169.42
Exp/Cntr=0.3,0.1

Type RM Length L Ch R = 1 ,30468.58,248.990600,248.990600,248.990600
XS GIS Cut Line= 6
853800.038106804 847604.39470896853870.108034417847595.235372131
853938.286102017847591.871661276853975.126544225847591.565482161
853977.126544176847591.565985942854112.599622765847590.265765979
#Sta/Elev= 30
9823.231222.96719848.406213.21139858.491 208.3719868.576202.29919878.661195.2599
9893.897 185.0579898.674181.69469908.807174.1606 9918.82165.44069928.832156.9905
9938.844147.95779948.856138.19829958.868127.00239968.872118.56769978.873116.1704
9988.873114.39549998.873113.578910008.87113.875310018.87116.087210028.87132.5375
10038.88144.217610048.88 154.21810058.88162.058210068.88168.213610078.88174.6538
10088.88182.262710098.88188.576510108.88192.701310118.88195.683310136.48200.4071
#Mann= 3 , 0 , 0
9823.231    0.12       09823.231    0.12       010136.48    0.12       0
#XS Ineff= 2 , 0
       0                               0
Bank Sta=9823.231,10136.48
Exp/Cntr=0.3,0.1

Type RM Length L Ch R = 1 ,30219.59,248.990700,248.990700,248.990700
XS GIS Cut Line= 6
853792.120546032847868.811886867853873.108622699847855.121828356
853984.464092377847840.293885621853986.447168701847840.034254526
854081.236141402847827.927814011854147.425509957847817.674342335
#Sta/Elev= 30
9804.525235.62099817.587224.97099827.729220.70559837.871215.53659848.012211.2238
9858.154205.80169868.296200.01799878.438192.8942 9888.57186.79029898.658181.5808
9918.835169.87479939.011154.43539949.099145.06229959.188134.14949969.276121.0427
9979.364113.79559989.452110.3321 9999.54109.709610009.62109.9743 10019.7110.7802
10039.87117.915810060.03133.772910080.19148.374110090.27154.777110100.37163.3776
10110.49171.293610120.61179.739910130.73185.841410140.84189.935410163.54195.5656
#Mann= 3 , 0 , 0
9804.525    0.12       09804.525    0.12       010163.54    0.12       0
#XS Ineff= 2 , 0
       0                               0
Bank Sta=9804.525,10163.54
Exp/Cntr=0.3,0.1

Type RM Length L Ch R = 1 , 29970.6,248.990600,248.990600,248.990600
XS GIS Cut Line= 6
853860.573637513848124.002724515853948.610721152848101.380531792
854089.449755652  848072.3174174854124.224534275848062.205320306
854153.734305326848050.842978175854161.231637666848047.088239132
#Sta/Elev= 30
9825.607184.90129836.229181.04469840.641178.90739850.949172.55689861.257  163.34
9871.565154.91839892.181149.10679902.489143.83829912.797135.04269923.035125.7674
9933.234120.51129943.433116.46259953.631114.3675 9963.83112.85519974.029109.9633
9984.228108.14479994.427107.339210014.86107.125810025.09110.793210035.32118.8643
10045.55  130.1710066.11146.078410076.52152.375710086.94155.676710097.37162.1562
10108.09168.0888 10116.6175.631310118.81177.874910129.58185.728810136.55189.2757
#Mann= 3 , 0 , 0
9825.607  0.1122       09825.607  0.1122       010136.55  0.1122       0
#XS Ineff= 2 , 0
       0                               0
Bank Sta=9825.607,10136.55
Exp/Cntr=0.3,0.1

Type RM Length L Ch R = 1 ,29721.61,248.990700,248.990700,248.990700
XS GIS Cut Line= 6
854058.531397344848435.022502258854093.647176126848368.156207524
854122.179123948848299.806692891854147.409818822848208.040681949
854178.084368163848153.093551186854209.969388164848109.990587558
#Sta/Elev= 30
9861.089214.0449 9872.63206.90359874.296205.2795 9883.89195.20539896.056181.7668
9906.408172.57219917.668161.96579928.927149.84259936.633140.22989940.055 136.605
9961.739130.97919966.016125.84239972.581  117.159983.422 107.108 10010.7106.3312
10015.64106.339210025.92107.238110036.19 109.89210046.47114.7082 10077.3132.9526
10087.89 137.34710098.59144.399410109.41148.964910120.53 154.48310143.55164.9912
10169.02175.215210198.53187.7427 10203.4189.629710216.23193.110210222.66196.3724
#Mann= 3 , 0 , 0
9861.089  0.0748       09861.089  0.0748       010222.66  0.0748       0
#XS Ineff= 2 , 0
       0                               0
Bank Sta=9861.089,10222.66
Exp/Cntr=0.3,0.1

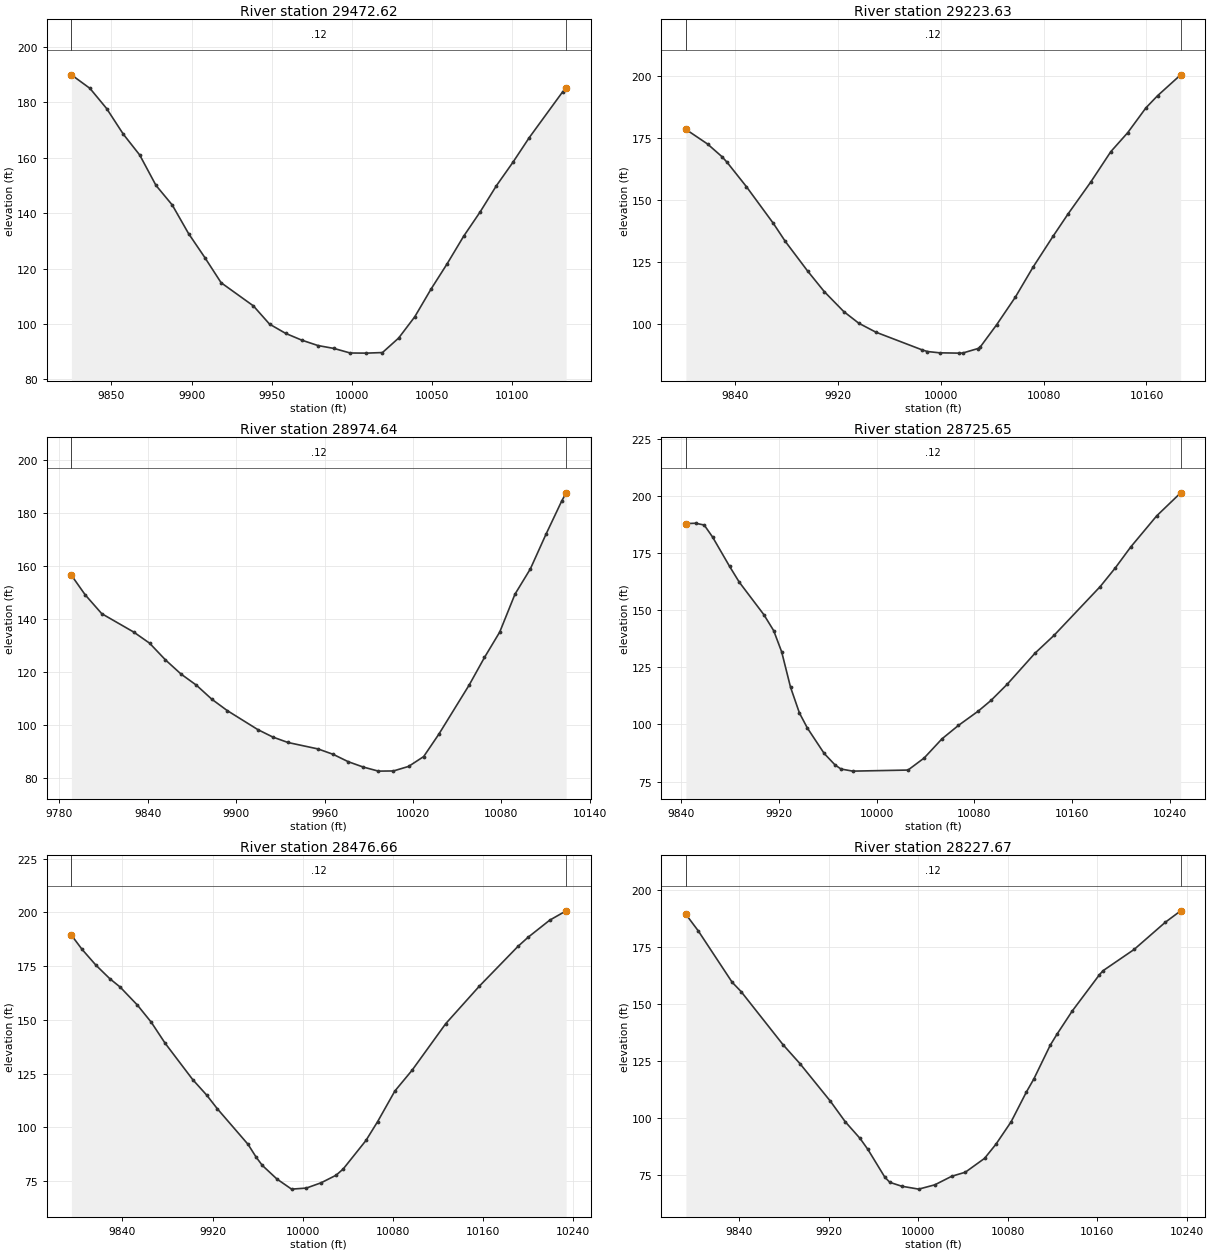
Type RM Length L Ch R = 1 ,29472.62,248.990600,248.990600,248.990600
XS GIS Cut Line= 6
854325.187698622 848456.12555464854334.714140333848423.378148601
854345.717538075848363.463634537854361.556733084848234.431897791
854375.280470282848169.305002836854380.453521445 848152.81571128
#Sta/Elev= 30
9825.008189.93679836.595185.0437 9847.01177.76339857.424168.50639867.632161.0138
9877.799150.04249887.966142.95319898.133132.65359908.301123.98779918.468   114.9
9938.621106.5348 9948.6999.965989958.75996.611699968.82994.169529978.89892.22957
9988.96791.171859999.03689.5364410009.1289.48892 10019.289.6987810029.2994.92971
10039.37102.617310049.46112.555610059.67121.833710069.89131.698410080.11140.4081
10090.33149.924110100.55158.302810110.77167.231810131.58183.733210133.87185.2572
#Mann= 3 , 0 , 0
9825.008    0.12       09825.008    0.12       010133.87    0.12       0
#XS Ineff= 2 , 0
       0                               0
Bank Sta=9825.008,10133.87
Exp/Cntr=0.3,0.1

Type RM Length L Ch R = 1 ,29223.63,248.990600,248.990600,248.990600
XS GIS Cut Line= 6
854453.903842946 848516.10488062854575.748221083848377.429957677
854584.585297632848368.015262596854585.984471009 848366.58616717
854675.745463277848270.810336411854714.047960861848232.221906814
#Sta/Elev= 30
9801.489178.5148  9818.3172.64429829.583 167.508 9833.45165.3043  9848.6  155.42
9869.518 140.6449878.901133.31479896.141121.45999909.202113.09269924.352105.0509
9936.076 100.3399949.38796.730099984.95489.67333 9989.42 88.9376    999988.40356
10014.18 88.282810016.8888.3082910028.8190.1308810030.5890.7365110043.4399.77091
10057.99110.9169 10071.7122.9558 10087.3135.434410099.11144.533810116.55157.2307
10132.26169.5611 10145.4 177.201 10159.6187.228710168.63192.105510186.63200.5338
#Mann= 3 , 0 , 0
9801.489    0.12       09801.489    0.12       010186.63    0.12       0
#XS Ineff= 2 , 0
       0                               0
Bank Sta=9801.489,10186.63
Exp/Cntr=0.3,0.1

Type RM Length L Ch R = 1 ,28974.64,248.990700,248.990700,248.990700
XS GIS Cut Line= 6
854496.763416249 848647.36160961854518.594645919848635.940541573
854561.633241236848618.883859264854612.510109668848603.962512065
854735.327547331848577.266753164  854817.8710272848552.875486378
#Sta/Elev= 30
 9788.18156.52349797.476149.18729808.762142.04819830.465 135.1199841.222130.9376
9851.979124.65139862.623119.27999873.044115.09659883.465109.82749893.886105.5669
9914.68198.384539924.91395.568739935.14593.525049955.60891.088929965.83989.06128
9976.071 86.28569986.30384.263629996.53482.7385510006.7782.8081210017.0184.51178
10027.2588.2221510037.4896.5993910058.18115.218410068.52125.553710078.87135.1274
10089.22149.388910099.65158.902910110.28171.981710120.91184.448610123.96 187.561
#Mann= 3 , 0 , 0
 9788.18    0.12       0 9788.18    0.12       010123.96    0.12       0
#XS Ineff= 2 , 0
       0                               0
Bank Sta=9788.18,10123.96
Exp/Cntr=0.3,0.1

Type RM Length L Ch R = 1 ,28725.65,248.990600,248.990600,248.990600
XS GIS Cut Line= 6
854619.342506508848935.447010293854662.042177498 848893.96207432
854765.972929182848783.746759364 854812.22703342 848742.96818691
854875.951527894848694.096540488854918.020903435848663.451262269
#Sta/Elev= 30
9843.904187.81349851.792187.97279858.896187.18389865.734181.94189879.677169.0902
9887.598162.19249907.741147.97229915.777140.9758 9922.29131.73259929.545116.2726
9936.838104.98459943.313 98.42869957.08187.299779965.93582.302719970.84980.48117
9980.48479.5598210025.7480.0280810038.9285.2834110053.5193.6639410066.9799.53341
10083.28105.829810093.63110.460210106.96117.564410129.69131.130110145.29138.9485
 10183.1160.292810195.42168.4303 10208.1177.618810229.34191.215610248.95201.2727
#Mann= 3 , 0 , 0
9843.904    0.12       09843.904    0.12       010248.95    0.12       0
#XS Ineff= 2 , 0
       0                               0
Bank Sta=9843.904,10248.95
Exp/Cntr=0.3,0.1

Type RM Length L Ch R = 1 ,28476.66,248.990600,248.990600,248.990600
XS GIS Cut Line= 6
854829.948962561849082.752804276854924.849531205848949.371905245
854950.741349524848918.201267533855014.628576474848844.470832317
855063.967117712848789.687637173855108.844748951848744.662263502
#Sta/Elev= 30
9794.782189.37139804.297182.7357 9816.57175.40859828.842169.14029837.993165.2641
9853.388 156.8389865.661148.87749877.934139.1394 9902.48122.17789914.753115.0519
9924.239108.66979951.57192.076549958.71486.151599964.16282.326779977.16275.97865
9990.16271.2682910003.2571.7516210016.4874.2388110029.7177.7457710036.0380.66653
10056.1793.8885810066.58   102.710081.85116.906210097.11126.5505   10127148.2353
10156.89 165.70810191.02184.125410200.08 188.40210219.26196.348810233.86200.6922
#Mann= 3 , 0 , 0
9794.782    0.12       09794.782    0.12       010233.86    0.12       0
#XS Ineff= 2 , 0
       0                               0
Bank Sta=9794.782,10233.86
Exp/Cntr=0.3,0.1

Type RM Length L Ch R = 1 ,28227.67,248.990700,248.990700,248.990700
XS GIS Cut Line= 6
854997.739487654849242.115655249855134.006303247849086.710946916
855135.344719246849085.224796595855139.380516755849080.752550158
855239.749696396848972.748250485855295.641561975848915.115653284
#Sta/Elev= 30
9792.314189.39929803.326182.17239833.662159.57039841.677155.46139879.165132.1136
9894.333123.76879921.476107.29639934.77698.261589948.076 90.89089955.00486.11221
9970.17273.894679974.676 71.60289985.33969.8984910000.4868.6240510014.8870.51184
10029.9774.2704610042.1876.0579310059.3582.1374910069.4888.3180710083.1398.22841
10096.79111.330210103.42117.031510118.11131.894910124.09136.687110137.74 146.899
10162.01162.814210165.26164.620210193.12173.981110220.98185.924610234.75190.9618
#Mann= 3 , 0 , 0
9792.314    0.12       09792.314    0.12       010234.75    0.12       0
#XS Ineff= 2 , 0
       0                               0
Bank Sta=9792.314,10234.75
Exp/Cntr=0.3,0.1