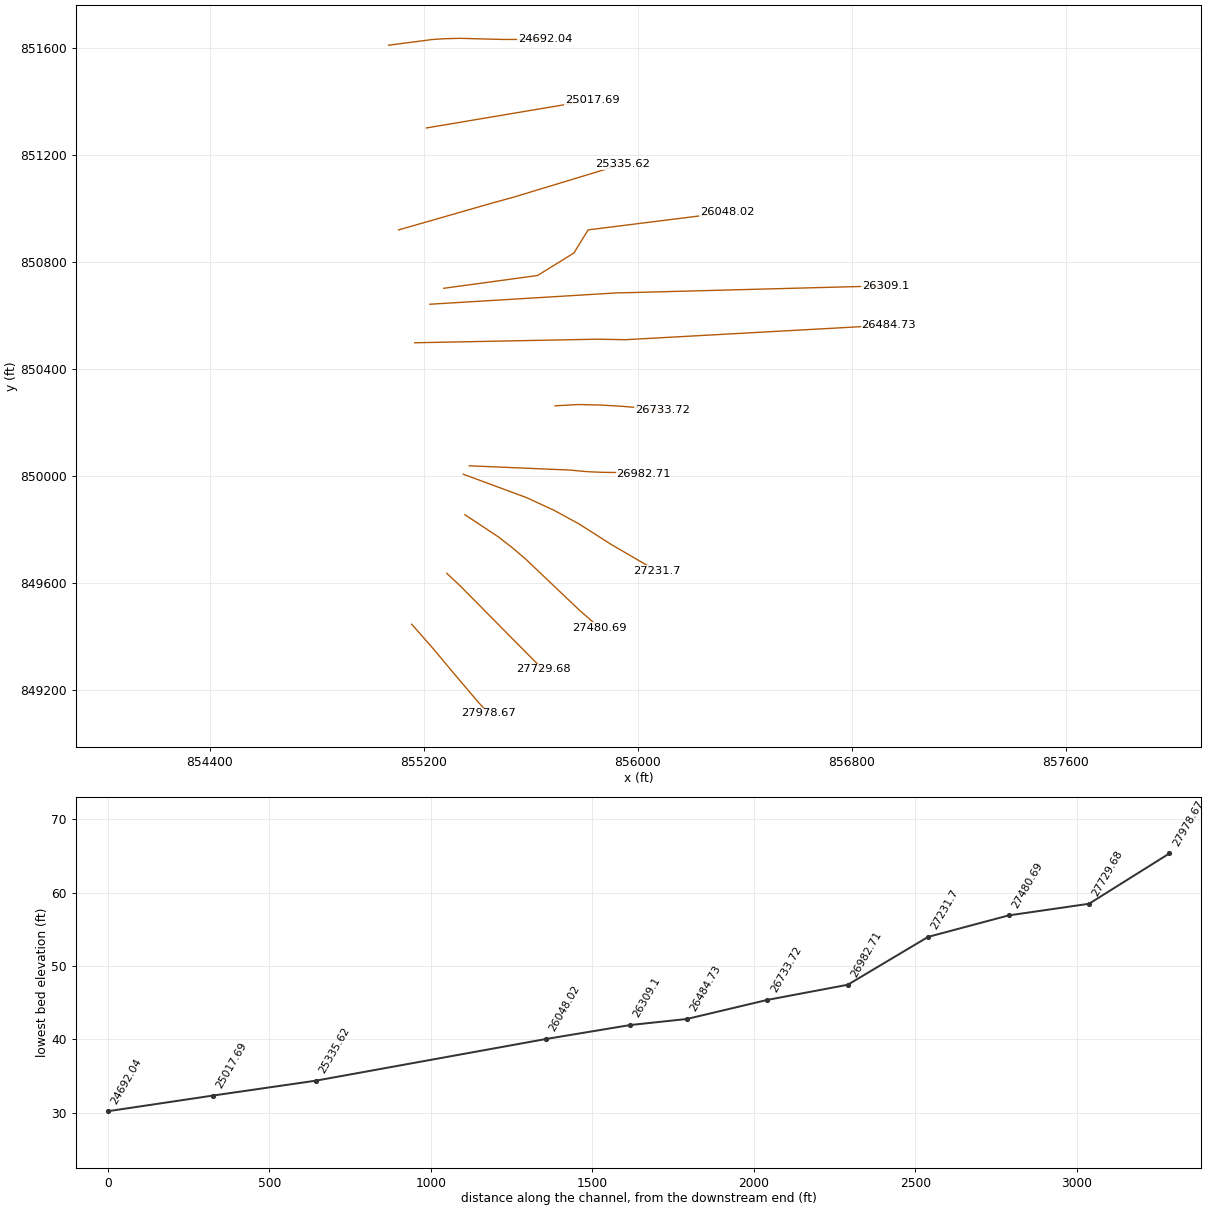
HEC-RAS study 18726_ras.prj: 18726

--- 18726_ras.g01 (geometry) --- (continued)

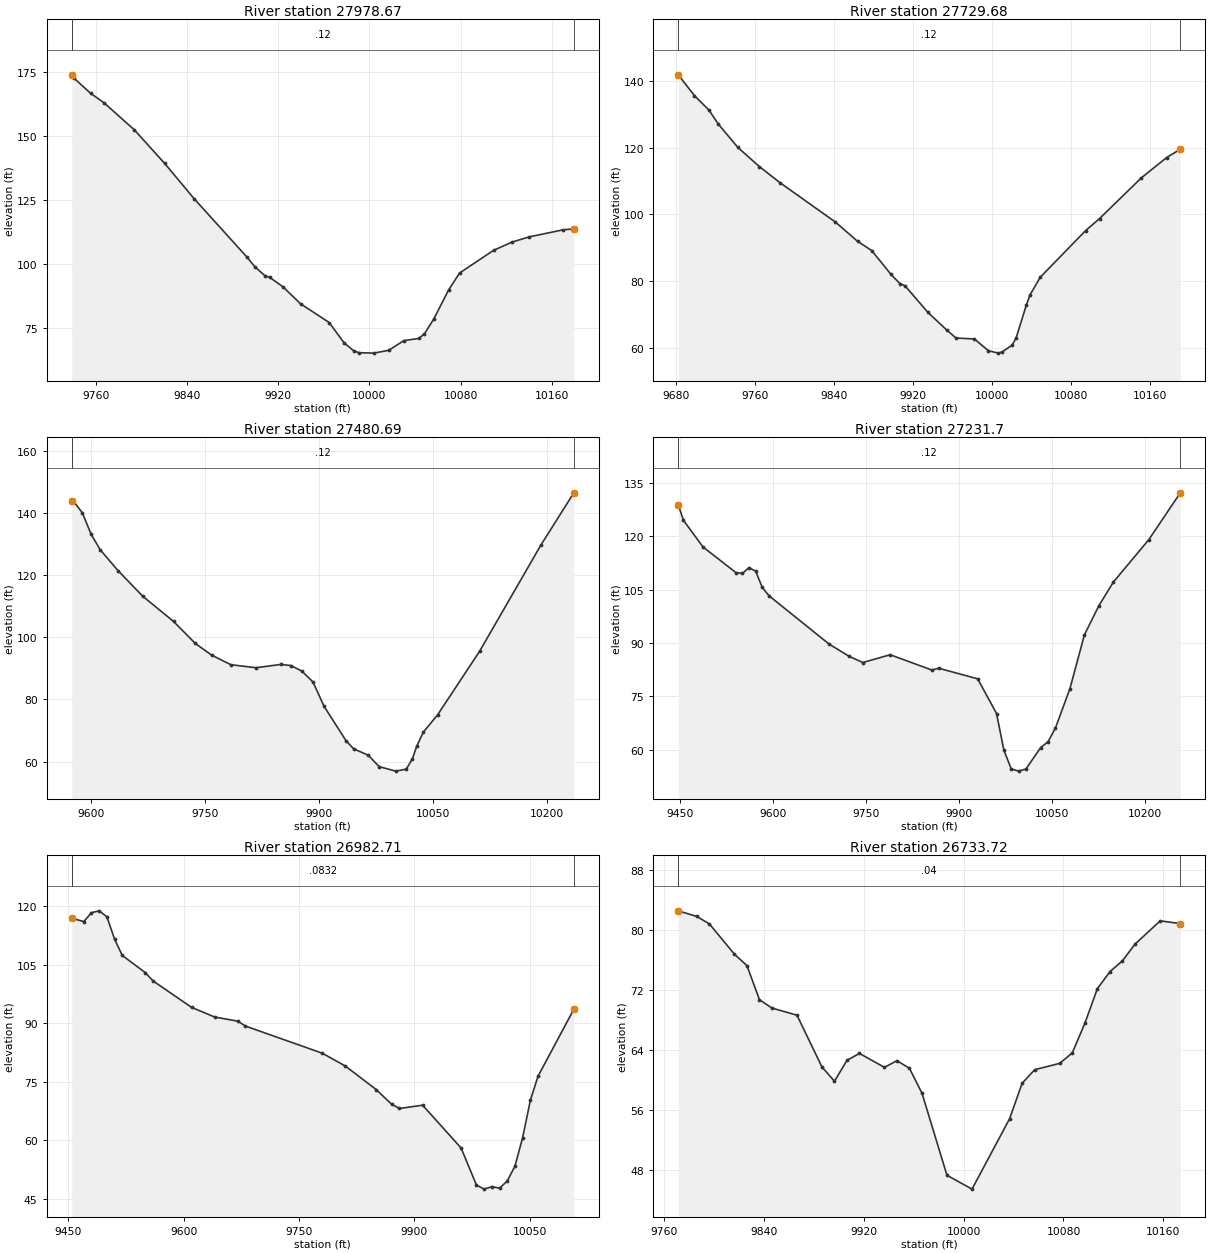
Type RM Length L Ch R = 1 ,27978.67,248.990600,248.990600,248.990600
XS GIS Cut Line= 6
855153.802411562 849445.93141145 855162.09560385849437.139731365
855233.370725838849356.072935868855324.363219659849247.179172567
855406.492206214849150.821930717855441.277452376849112.727016203
#Sta/Elev= 30
9739.063174.03319740.808 172.7949755.548166.83099767.314163.11799793.945152.5337
9820.576139.40759846.416125.60359892.823102.75689899.58999.066589908.41795.57213
9912.62194.920589924.01191.311269939.60584.62692 9964.7577.287019977.783 69.3736
9986.38866.189799990.81565.5286510003.8665.34759   1001766.4579710030.1470.22639
10043.2871.0796110048.2372.9004310056.4278.6685410069.5690.1407910079.0696.63939
10108.98105.541210125.31108.754510140.23110.763210169.89113.5073 10179.2113.8735
#Mann= 3 , 0 , 0
9739.063    0.12       09739.063    0.12       0 10179.2    0.12       0
#XS Ineff= 2 , 0
       0                               0
Bank Sta=9739.063,10179.2
Exp/Cntr=0.3,0.1

Type RM Length L Ch R = 1 ,27729.68,248.990700,248.990700,248.990700
XS GIS Cut Line= 6
855285.401869504849636.235474216855335.710653089849589.245241613
855509.951650769849412.983514074 855511.35376836849411.557307111
  855638.3233828849283.433849041855644.929936634849277.069044164
#Sta/Elev= 30
9682.312141.76269698.772135.52139713.422131.20839722.813127.05379742.722120.0204
9764.367114.32549785.245109.4984 9841.4997.684669863.93791.924449878.16289.18332
9897.73582.02449 9906.6179.319039911.79778.659799935.05970.677739953.98165.43037
9963.50863.011969982.10362.721759996.16559.2347710006.1858.4850910010.2358.83756
10020.3960.9032410024.3162.9998110034.5972.7538110038.3975.90226 10048.881.20921
 10094.795.1490610108.7898.7468510151.02110.902810176.66117.000310190.55119.4928
#Mann= 3 , 0 , 0
9682.312    0.12       09682.312    0.12       010190.55    0.12       0
#XS Ineff= 2 , 0
       0                               0
Bank Sta=9682.312,10190.55
Exp/Cntr=0.3,0.1

Type RM Length L Ch R = 1 ,27480.69,248.990600,248.990600,248.990600
XS GIS Cut Line= 6
855353.208042291849855.360859165855479.543668713849771.784186004
855532.932273257 849729.99895943 855582.22433099849687.739769128
855782.723980576849497.147123452855857.732671643849431.838167385
#Sta/Elev= 30
9574.844144.00829576.946144.01739588.675140.23469600.404133.22719612.134128.3466
9635.593121.58129668.227113.29239708.666105.18979737.39198.06395 9758.7194.32351
9784.10791.214059817.225 90.24479849.59191.298739863.08490.951289877.59989.14155
9892.11485.63744 9906.6377.82138 9935.6666.662099945.71664.07193 9964.6962.04222
9979.20558.33963   1000156.8981910014.7357.5324510022.7260.8057310028.5264.89517
10037.2369.4616210056.1175.0840510111.2995.5737910191.88129.8181 10235.2146.6506
#Mann= 3 , 0 , 0
9574.844    0.12       09574.844    0.12       0 10235.2    0.12       0
#XS Ineff= 2 , 0
       0                               0
Bank Sta=9574.844,10235.2
Exp/Cntr=0.3,0.1

Type RM Length L Ch R = 1 , 27231.7,248.990600,248.990600,248.990600
XS GIS Cut Line= 6
855346.922145779850006.909332782855582.889637279849919.711157116
855686.111109214849872.099915743855780.227455001849820.741142601
 855901.79989561 849743.15771881856069.216064804849646.131844433
#Sta/Elev= 30
9447.471 128.832 9455.92124.44649487.523116.95539540.422109.79089551.002109.5171
9561.609111.15259572.361110.18719583.114105.58139593.866103.27449690.63989.71577
9723.47286.205679745.49784.494679789.54786.682429856.68982.385559867.976 82.8852
9930.75679.911959961.20270.156519973.04259.857379984.88154.611959996.72153.97518
10008.6254.5695310032.39  60.58410044.2862.2297710056.1766.0585710079.6577.16391
10102.97 92.248310126.29100.459910149.61107.072910207.05119.052510257.77 132.183
#Mann= 3 , 0 , 0
9447.471    0.12       09447.471    0.12       010257.77    0.12       0
#XS Ineff= 2 , 0
       0                               0
Bank Sta=9447.471,10257.77
Exp/Cntr=0.3,0.1

Type RM Length L Ch R = 1 ,26982.71,248.990700,248.990700,248.990700
XS GIS Cut Line= 6
855369.381106546850038.343379328855744.430356617850022.426114683
855808.329606146850016.554404133855864.343519862 850013.95737036
855948.842051173850012.850031586856021.353401724  850006.9211432
#Sta/Elev= 30
9454.335116.93799469.968116.09549479.977 118.3649489.986118.84789499.995117.3229
9510.004111.57669520.013107.3974 9550.04102.98669560.049100.85969610.09494.08185
9640.121 91.60529670.14890.544769680.15789.286549780.24782.310699810.27479.00287
9850.37872.965439870.46369.192239880.50568.142639910.57968.981489960.62258.00048
9980.62348.491249990.62347.4490710000.62  48.08610010.6347.7019510020.6349.53101
10030.6353.3432510040.6460.6344910050.6770.2027510060.6976.4197610107.2593.61057
#Mann= 3 , 0 , 0
9454.335  0.0832       09454.335  0.0832       010107.25  0.0832       0
#XS Ineff= 2 , 0
       0                               0
Bank Sta=9454.335,10107.25
Exp/Cntr=0.3,0.1

Type RM Length L Ch R = 1 ,26733.72,248.990600,248.990600,248.990600
XS GIS Cut Line= 6
855690.080560984  850262.5657538855777.475911026 850267.39825248
855863.414466064 850265.33642875855946.879855488850260.327641533
856031.413050751850252.896613332 856090.99523127850246.008068801
#Sta/Elev= 30
9771.56982.518619786.51181.762199796.52780.768489816.55776.737139826.57275.20507
9836.58870.661199846.603 69.54529866.62468.59405 9886.6361.686819896.63359.78063
9906.636 62.56269916.63863.497069936.64461.633069946.64962.522169956.66361.50917
9966.678 58.19969986.70647.2348210006.75 45.384810036.8354.7689810046.8759.50396
10056.9161.3180910076.9962.1672110087.0263.5596910097.0667.48859 10107.172.12357
10117.1574.3953610127.2275.8508310137.2878.0774710157.4281.1836310173.5280.81441
#Mann= 3 , 0 , 0
9771.569    0.04       09771.569    0.04       010173.52    0.04       0
#XS Ineff= 2 , 0
       09958.891        10046.79       0
Bank Sta=9771.569,10173.52
Exp/Cntr=0.3,0.1

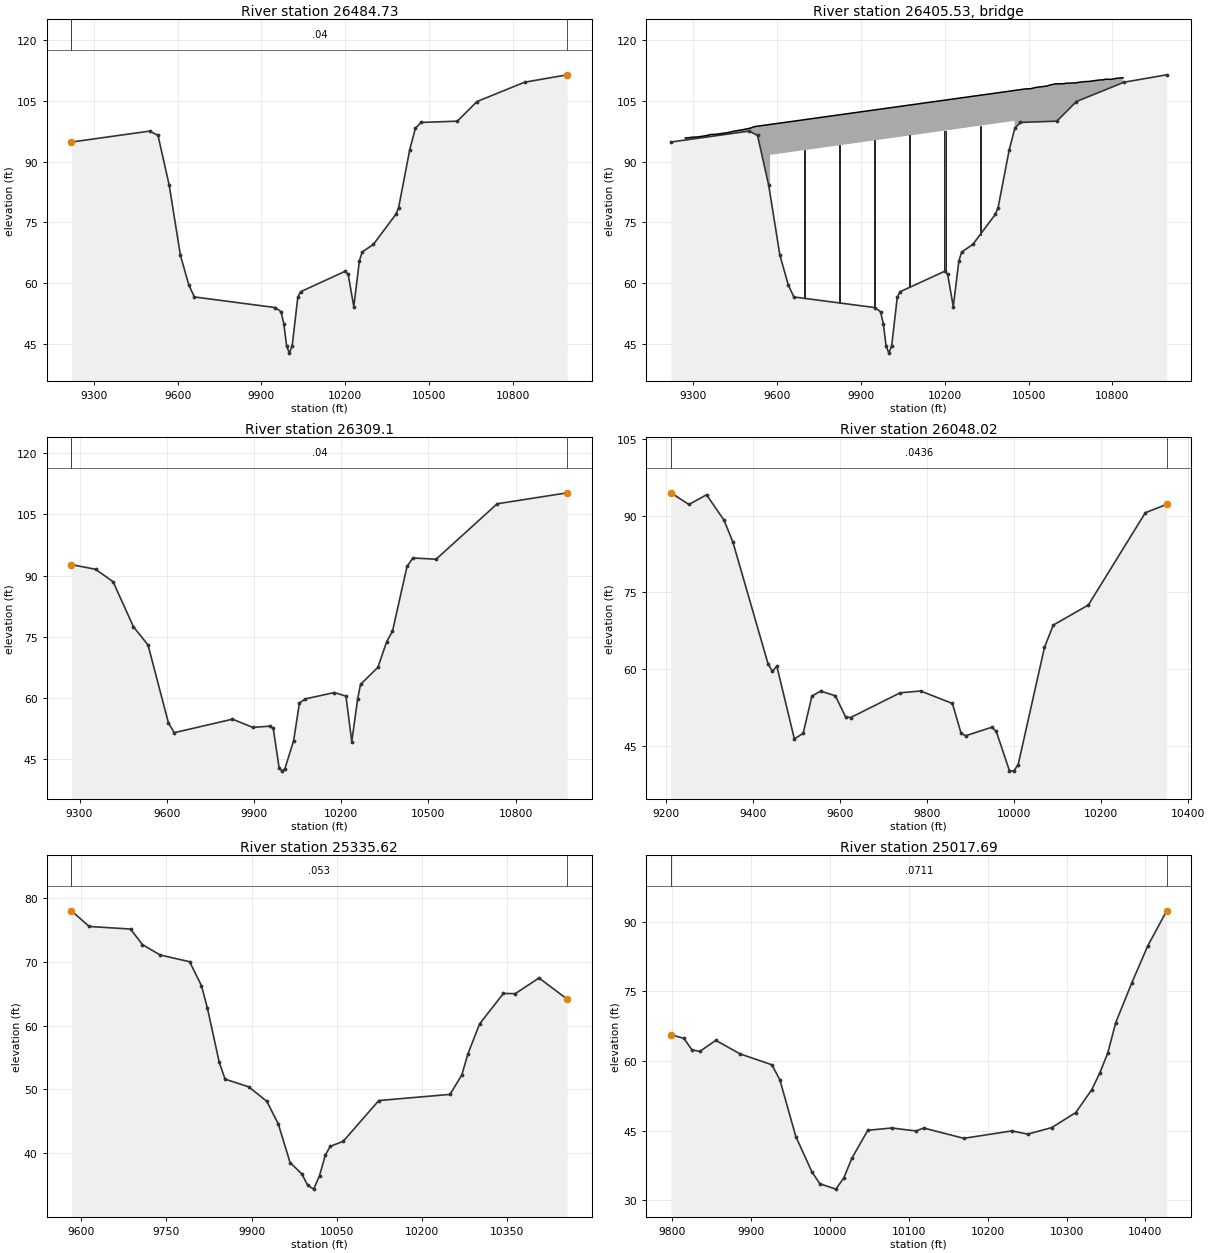
Type RM Length L Ch R = 1 ,26484.73,175.632700,175.632700,175.632700
XS GIS Cut Line= 5
855165.295640333850498.274325178855847.015324919850511.705735015
855952.097097994   850509.768734855954.097083268 850509.76873224
856937.283862436850564.231834032
#Sta/Elev= 30
9220.326 94.82549500.08597.524149530.09196.450129570.09984.174749610.10666.94166
9640.11259.610279660.11656.636079950.17154.015229970.17552.997999980.17650.05066
9990.178 44.516210000.1842.7871910010.1844.6536710030.2156.5831510040.2357.92501
10200.4762.9920110210.4962.1849110230.5254.2419810250.5565.5359310260.57 67.7209
10300.6369.5939810380.7576.9840510390.7678.6153310430.8392.9831910450.8698.21296
10470.89 99.663910601.0999.9719510671.19 104.80610841.45109.576410993.97111.3976
#Mann= 3 , 0 , 0
9220.326    0.04       09220.326    0.04       010993.97    0.04       0
#XS Ineff= 2 , 0
       09945.182        10041.52       0
Bank Sta=9220.326,10993.97
Exp/Cntr=0.3,0.1

Type RM Length L Ch R = 3 ,26405.53,,,
BEGIN DESCRIPTION:
END DESCRIPTION:
Bridge Culvert--1,0,-1,-1, 0
Deck Dist Width WeirC Skew NumUp NumDn MinLoCord MaxHiCord MaxSubmerge Is_Ogee
65.816350,44.000000,2.6,0, 33, 33, , , 0.95, 0, 0,0,,
 9271.71 9275.72 9295.73 9315.73 9345.73 9365.74 9375.74 9425.74 9445.74 9475.75
 9505.75 9519.02 9575.17 9575.1710450.1710450.1710489.2510505.9910525.9910566.00
10576.0010596.0110626.0210636.0210666.0310696.0310716.0410756.0510766.0510776.06
10796.0610816.0710837.75
   95.84   95.82   96.01   96.08   96.39   96.74   96.69   97.16   97.51   97.84
   98.28   98.63   99.16   99.16  107.55  107.55  107.93  107.96  108.29  108.64
  108.88  109.17  109.21  109.33  109.40  109.70  109.77  110.15  110.15  110.33
  110.28  110.55  110.67
 -904.16 -904.18 -903.99 -903.92 -903.61 -903.26 -903.31 -902.84 -902.49 -902.16
 -901.72 -901.37 -900.84   91.66  100.05 -892.45 -892.07 -892.04 -891.71 -891.36
 -891.12 -890.83 -890.79 -890.67 -890.60 -890.30 -890.23 -889.85 -889.85 -889.67
 -889.72 -889.45 -889.33
 9271.71 9275.72 9295.73 9315.73 9345.73 9365.74 9375.74 9425.74 9445.74 9475.75
 9505.75 9519.02 9561.79 9561.7910436.7910436.7910489.2510505.9910525.9910566.00
10576.0010596.0110626.0210636.0210666.0310696.0310716.0410756.0510766.0510776.06
10796.0610816.0710837.75
   95.84   95.82   96.01   96.08   96.39   96.74   96.69   97.16   97.51   97.84
   98.28   98.63   99.04   99.04  107.43  107.43  107.93  107.96  108.29  108.64
  108.88  109.17  109.21  109.33  109.40  109.70  109.77  110.15  110.15  110.33
  110.28  110.55  110.67
 -904.16 -904.18 -903.99 -903.92 -903.61 -903.26 -903.31 -902.84 -902.49 -902.16
 -901.72 -901.37 -900.96   91.54   99.93 -892.57 -892.07 -892.04 -891.71 -891.36
 -891.12 -890.83 -890.79 -890.67 -890.60 -890.30 -890.23 -889.85 -889.85 -889.67
 -889.72 -889.45 -889.33
Pier Skew, UpSta & Num, DnSta & Num=  ,9698.74, 2 ,9685.36, 2 , 0 , 0 , 0 ,,
    4.00    4.00
 -899.65  100.35
    4.00    4.00
 -899.78  100.22
Pier Skew, UpSta & Num, DnSta & Num=  ,9824.31, 2 ,9810.94, 2 , 0 , 0 , 0 ,,
    4.00    4.00
 -898.45  101.55
    4.00    4.00
 -898.58  101.42
Pier Skew, UpSta & Num, DnSta & Num=  ,9949.89, 2 ,9936.51, 2 , 0 , 0 , 0 ,,
    4.00    4.00
 -897.24  102.76
    4.00    4.00
 -897.37  102.63
Pier Skew, UpSta & Num, DnSta & Num=  ,10075.46, 2 ,10062.08, 2 , 0 , 0 , 0 ,,
    4.00    4.00
 -896.04  103.96
    4.00    4.00
 -896.17  103.83
Pier Skew, UpSta & Num, DnSta & Num=  ,10201.03, 2 ,10187.65, 2 , 0 , 0 , 0 ,,
    4.00    4.00
 -894.83  105.17
    4.00    4.00
 -894.96  105.04
Pier Skew, UpSta & Num, DnSta & Num=  ,10326.60, 2 ,10313.22, 2 , 0 , 0 , 0 ,,
    4.00    4.00
 -893.63  106.37
    4.00    4.00
 -893.76  106.24
BR Coef=-1 , 0 , 0 ,, 0 ,,,0.8,0,1,0,
WSPro=,,,, 1 ,,,, 0 ,,,, 0 ,,,,-1 ,-1 ,-1 , 0 , 0 , 0 , 0 , 0
BC Design=,, 0 ,, 0 ,,,,,,

Type RM Length L Ch R = 1 , 26309.1,261.075800,261.075800,261.075800
XS GIS Cut Line= 4
 855222.07382195850642.382879611855923.057047944850684.846334431
  855969.3532455850685.810429443856925.693627244850711.229554042
#Sta/Elev= 30
9272.28792.688879355.36591.530269415.47588.481449485.60377.402889535.69572.94872
9605.82353.82758 9625.8651.401319826.22754.719829896.35552.692959956.46553.01946
9966.48352.449269986.501 42.83969996.50341.9599410006.51 42.571610036.5149.42849
10056.5258.6884910076.5359.6901310176.5661.2608810216.5860.3822810236.5849.19487
10256.5959.6040610266.5963.2592810326.6267.4714610356.6373.7477810376.6376.31688
10426.65 92.249510446.6694.3027910526.6994.0151310736.76107.620610977.54110.3137
#Mann= 3 , 0 , 0
9272.287    0.04       09272.287    0.04       010977.54    0.04       0
#XS Ineff= 2 , 0
       09924.826        10038.79       0
Bank Sta=9272.287,10977.54
Exp/Cntr=0.3,0.1

Type RM Length L Ch R = 1 ,26048.02,712.403200,712.403200,712.403200
XS GIS Cut Line= 5
855273.886568947850701.963895721855624.804894925850749.755833392
855760.518023737850833.733670298855813.689109078850920.308921326
856333.615239365 850985.43854081
#Sta/Elev= 30
9211.089 94.43279252.58292.155079292.95294.059069333.32189.053839353.50584.80771
9434.24461.035979444.33659.538929454.42960.572679494.79846.352439514.98247.44234
9535.16754.727799555.35255.692049588.99654.771469612.515 50.65289624.27550.52831
9738.06355.363069785.00455.707939857.99653.275919878.15347.411789888.231 46.9639
  9948.748.630569958.77847.826919989.01240.167579999.09140.0546510009.1741.33261
10069.6464.2426110089.7968.5858610170.4272.5109210301.4490.5451710350.4392.17652
#Mann= 3 , 0 , 0
9211.089  0.0436       09211.089  0.0436       010350.43  0.0436       0
#XS Ineff= 2 , 0
       09840.297                       0
Bank Sta=9211.089,10350.43
Exp/Cntr=0.3,0.1

Type RM Length L Ch R = 1 ,25335.62,317.931900,317.931900,317.931900
XS GIS Cut Line= 6
855104.962338733850920.132142245855460.684058168851022.225561229
855505.144435073 851034.41856072855507.085129134851034.901992826
855542.553388656851044.821150311855942.423182753851166.052721447
#Sta/Elev= 30
9582.81678.002839614.06675.551059686.89275.145749707.69972.71556 9738.9171.08411
9790.92970.025299811.73666.26715 9822.1462.777489842.94754.291649853.351 51.6178
9894.96650.414869926.70648.150549946.98444.604399967.74338.551439988.48136.75338
 9998.8534.9710710009.22 34.3776 10019.636.4913810029.9939.7421610038.45 41.0879
10061.2841.8703410123.98 48.262810249.3849.2287210270.2752.2942910280.7255.54277
10301.6260.3060410343.4265.0464810364.3265.0257710406.1267.4774510455.6764.15852
#Mann= 3 , 0 , 0
9582.816   0.053       09582.816   0.053       010455.67   0.053       0
#XS Ineff= 2 , 0
       0                               0
Bank Sta=9582.816,10455.67
Exp/Cntr=0.3,0.1

Type RM Length L Ch R = 1 ,25017.69,325.646900,325.646900,325.646900
XS GIS Cut Line= 2
855208.840179919851301.351671073855828.644762218851405.688218573
#Sta/Elev= 30
9798.45965.674299814.84664.897969824.98762.416989835.12862.066819855.40964.46471
9885.83161.551069926.39459.190949936.53555.954989956.81643.698969977.09836.11286
9987.23833.5212510007.5232.3531610017.6634.76957 10027.838.9940310048.0845.05169
 10078.545.5432710108.9344.9094110119.07 45.531410169.7743.3145510230.6244.91205
 10250.944.2243610281.3245.6355710311.7448.8725310332.0253.8140610342.1657.40051
 10352.361.7256610362.4468.2947410382.73 76.837310403.0184.8428610426.9892.40493
#Mann= 3 , 0 , 0
9798.459  0.0711       09798.459  0.0711       010426.98  0.0711       0
#XS Ineff= 2 , 0
       0                               0
Bank Sta=9798.459,10426.98
Exp/Cntr=0.3,0.1

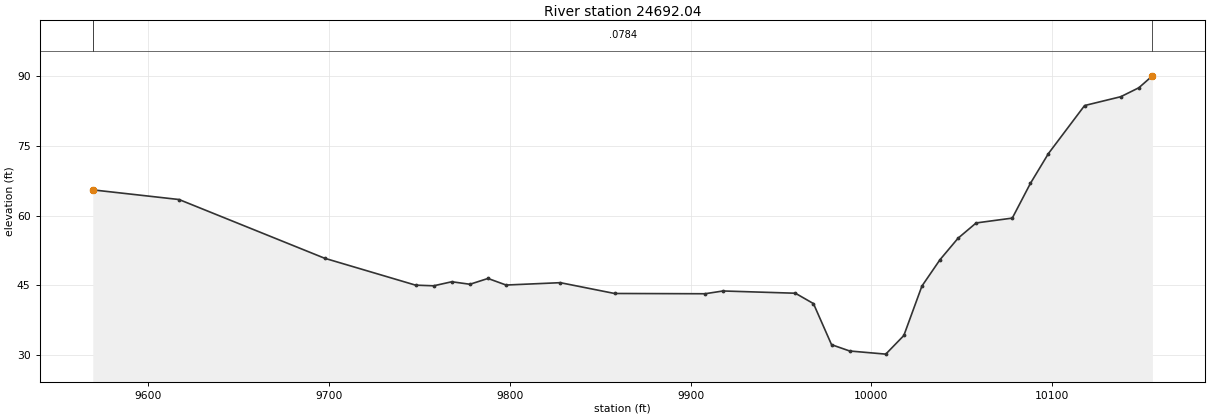
Type RM Length L Ch R = 1 ,24692.04,329.900300,329.900300,329.900300
XS GIS Cut Line= 6
 855067.85856085 851610.72490115855230.392145398851631.971188201
855276.703493268851635.067375372855335.483613041851636.465038345
855493.819549149851632.319752638855652.527828758851632.394357538
#Sta/Elev= 30
9569.24465.54198 9616.9863.464279697.55850.832179747.832 45.05119757.85444.91206
9767.87745.780849777.89945.241859787.90546.491299797.908 45.07539827.916 45.5819
9857.92643.259559907.94343.200839917.94743.79802 9957.9643.313939967.96441.08425
9977.96732.249749987.97130.8926410007.9730.2168410017.9734.2236410027.9744.85364
10037.9750.5256810047.97 55.149210057.9758.4272210077.9759.4704110087.9766.92198
10097.9773.3571810117.97 83.676810137.9785.5742210147.9787.49843 10155.590.06677
#Mann= 3 , 0 , 0
9569.244  0.0784       09569.244  0.0784       0 10155.5  0.0784       0
#XS Ineff= 2 , 0
       0                               0
Bank Sta=9569.244,10155.5
Exp/Cntr=0.3,0.1