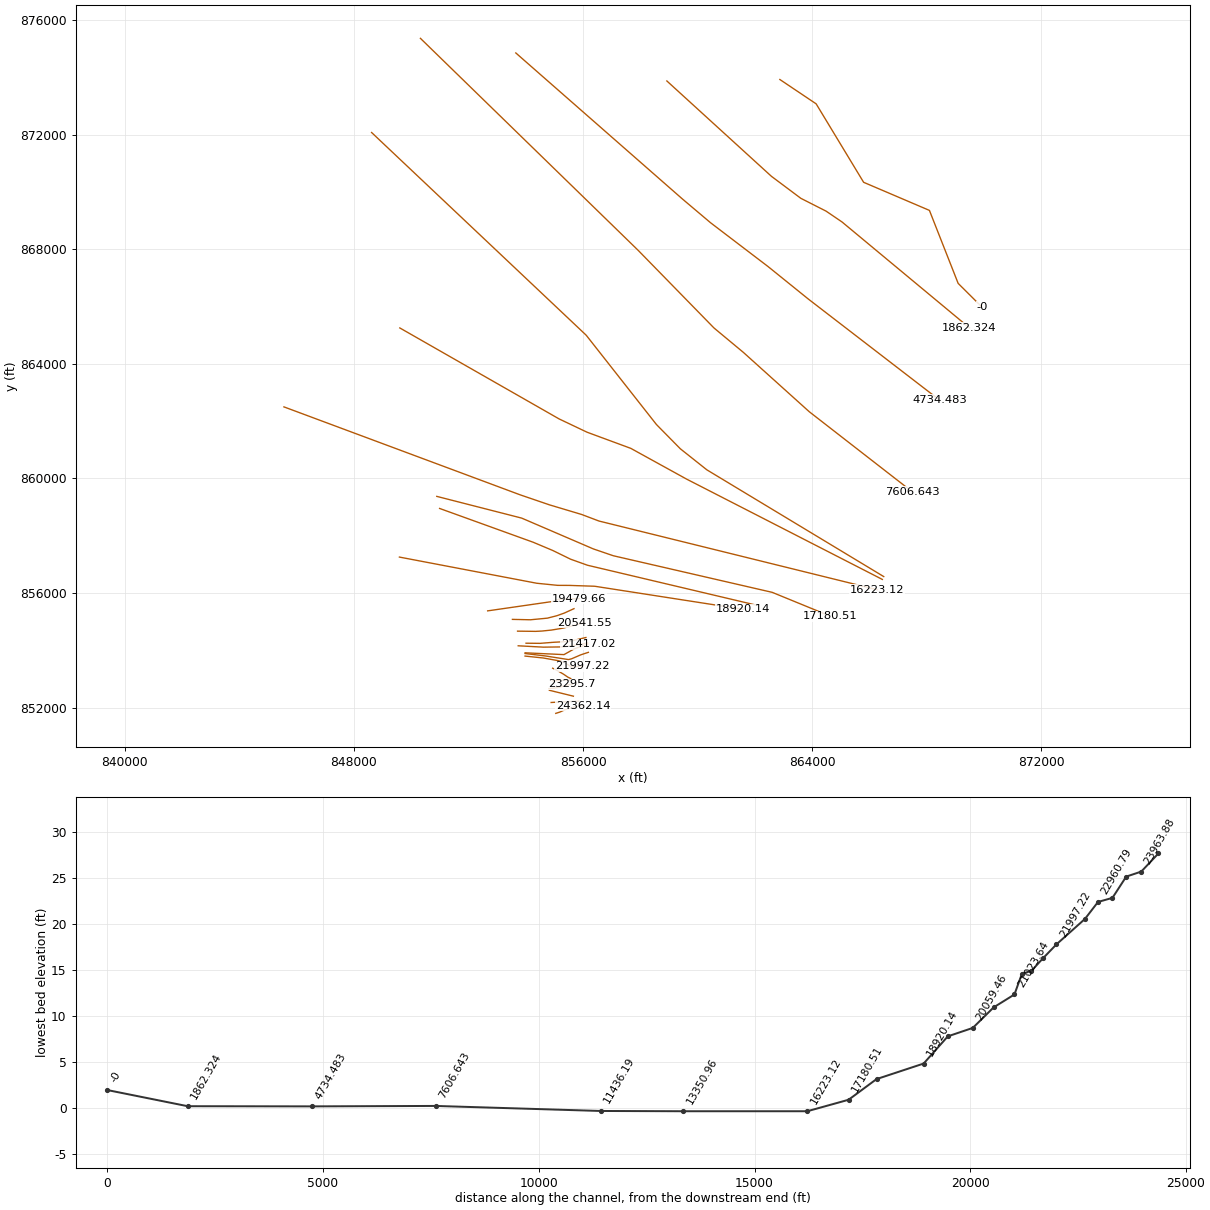
HEC-RAS study 18726_ras.prj: 18726

--- 18726_ras.g01 (geometry) --- (continued)

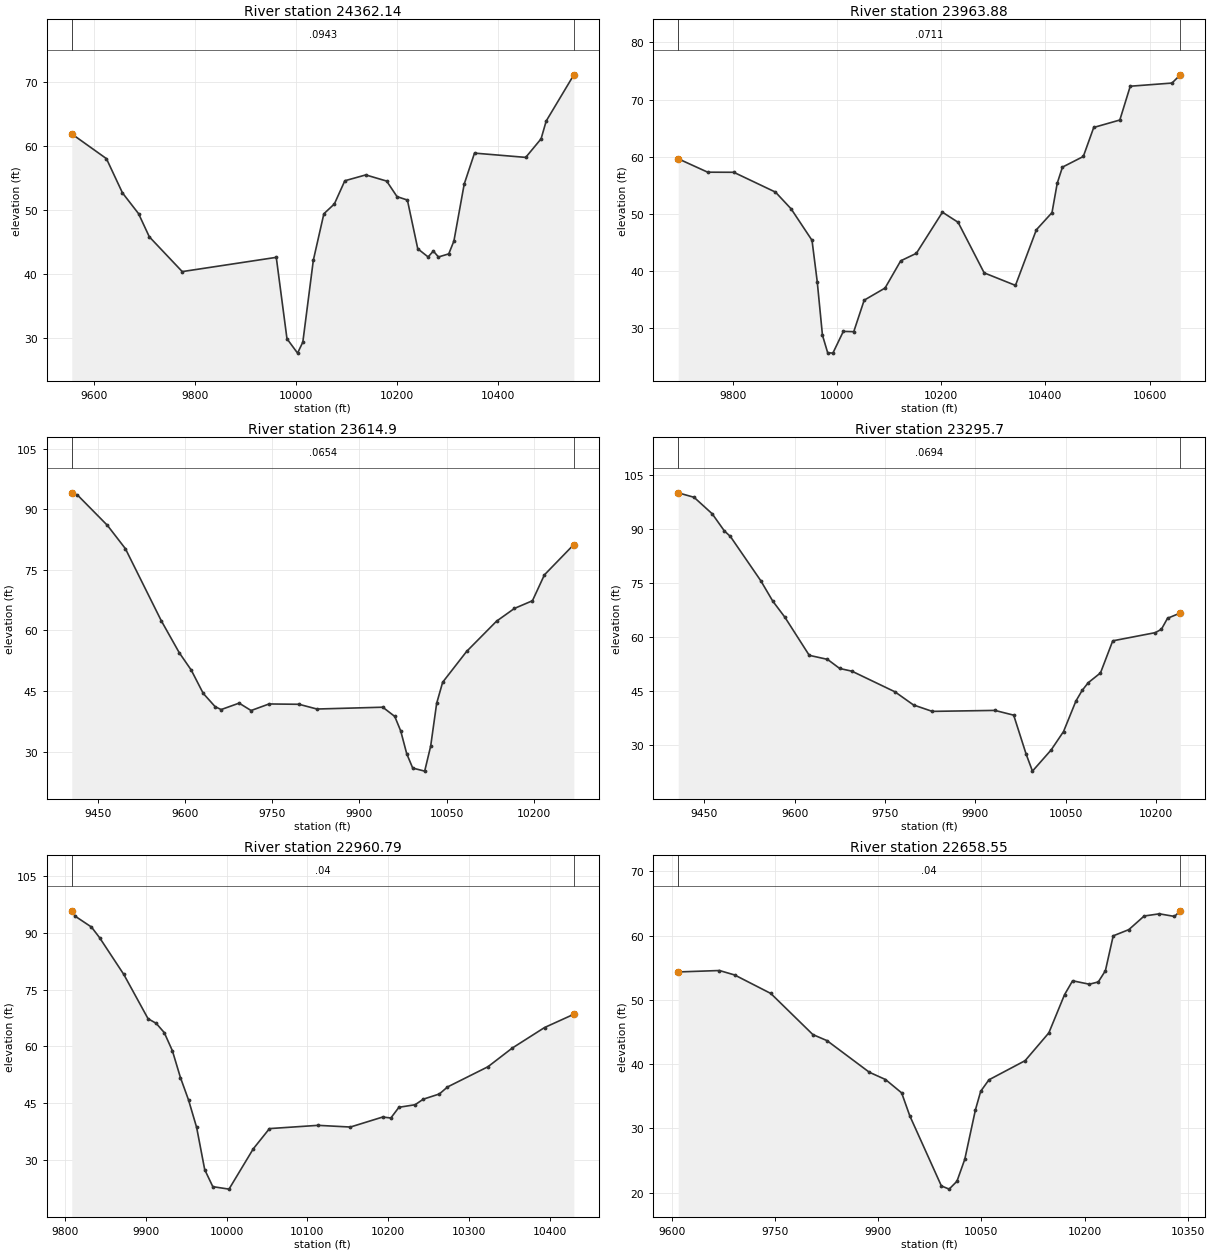
Type RM Length L Ch R = 1 ,24362.14,398.262400,398.262400,398.262400
XS GIS Cut Line= 6
855049.124263928 851796.51344327855194.885140545851843.580101945
855371.691646085 851923.77007339855463.399910083851956.879465615
 855725.34464168 852024.29601127855998.972044037852070.997294716
#Sta/Elev= 30
9556.036  61.9249624.62258.059759656.33452.706949688.17249.46059  9709.445.84724
9774.55540.407399960.55942.634299981.722  29.91310002.6727.6670210013.0729.38532
10033.8942.19722 10054.749.4454710075.4950.9831110096.1854.6045310137.5755.51854
 10178.954.5551110199.4152.1258110219.9251.5896510240.4343.9747210260.9442.69763
 10271.2 43.618210281.38 42.695410301.7543.1792310311.9345.18818 10332.354.08485
10352.6658.9257310453.9758.2563710484.3661.1589310494.4963.9435410549.1671.15938
#Mann= 3 , 0 , 0
9556.036  0.0943       09556.036  0.0943       010549.16  0.0943       0
#XS Ineff= 2 , 0
       0                10128.66       0
Bank Sta=9556.036,10549.16
Exp/Cntr=0.3,0.1

Type RM Length L Ch R = 1 ,23963.88,348.976400,348.976400,348.976400
XS GIS Cut Line= 2
854888.574542369852177.160508164855850.952315045852226.050315217
#Sta/Elev= 30
9695.34659.655399751.84457.313789801.90857.296669882.01253.83015 9912.0550.90064
9952.10245.406449962.11538.191089972.12828.834489982.14125.770619992.15425.69534
10012.1829.4939410032.2129.4444910052.2334.9476310092.28 37.067810122.3241.82296
10152.3643.1347510202.4250.3209210232.4648.5587210282.5339.71856 10342.637.53174
10382.66 47.2461 10412.750.2507210422.7155.3720710432.7258.1957710472.7760.05705
 10492.865.1316110542.8666.4298210562.8972.3370810642.9972.8889410658.9674.32731
#Mann= 3 , 0 , 0
9695.346  0.0711       09695.346  0.0711       010658.96  0.0711       0
#XS Ineff= 2 , 0
       0                10186.31       0
Bank Sta=9695.346,10658.96
Exp/Cntr=0.3,0.1

Type RM Length L Ch R = 1 , 23614.9,319.196800,319.196800,319.196800
XS GIS Cut Line= 2
854825.435172242852603.173399986855664.172257003 852396.93049748
#Sta/Elev= 30
9405.06694.038959414.91693.489049466.406 85.97829497.29980.219859559.08762.36558
 9589.9854.459169610.57650.168119631.17244.400079651.76841.095679662.06540.38809
9692.95941.980559713.55540.148319744.44941.774829795.93841.693649826.83240.52183
9940.10840.970399960.70438.689599971.00235.07675  9981.329.448439991.598 25.9035
10012.1925.1487710022.4931.3384910032.7941.9322710043.0947.1460910084.2854.77009
10135.7762.2628510166.6665.4295210197.5667.3217210218.1573.7295610268.7981.23947
#Mann= 3 , 0 , 0
9405.066  0.0654       09405.066  0.0654       010268.79  0.0654       0
#XS Ineff= 2 , 0
       09803.271                       0
Bank Sta=9405.066,10268.79
Exp/Cntr=0.3,0.1

Type RM Length L Ch R = 1 , 23295.7,334.915300,334.915300,334.915300
XS GIS Cut Line= 6
854808.816211774852661.137682695854963.795408172852675.431908935
855137.291411602852701.752688772855459.336626805852786.969673966
855549.285225067852803.488025783855626.111142051852811.706978805
#Sta/Elev= 30
9406.84899.959169433.098 98.72169463.22794.147829483.32389.416339493.37187.86692
9543.60975.653239563.70969.949759583.88665.47184 9624.2454.933159654.506 53.8127
9674.73451.289719695.053 50.5348 9766.4544.820559797.23441.177319828.35739.39969
9932.27139.670649963.44538.355579984.22827.492979994.61922.8443310025.6328.71593
 10046.233.8219110066.7742.2815410076.9845.1934510087.1547.3449510107.4950.05651
10127.8258.94606 10198.661.2222410208.6562.1733210218.7165.1927510239.9466.66586
#Mann= 3 , 0 , 0
9406.848  0.0694       09406.848  0.0694       010239.94  0.0694       0
#XS Ineff= 2 , 0
       09778.636                       0
Bank Sta=9406.848,10239.94
Exp/Cntr=0.3,0.1

Type RM Length L Ch R = 1 ,22960.79,302.237400,302.237400,302.237400
XS GIS Cut Line= 2
854930.709555313852932.783364753855551.147336334852961.759179538
#Sta/Elev= 30
9808.52795.753919812.82294.327689832.84491.487019842.85588.704259872.88778.98847
 9902.92 67.30649912.93166.106469922.94263.657549932.95358.898579942.96451.80117
9952.974 45.90269962.98538.665899972.99627.528819983.00723.0456810003.03 22.3961
10033.0633.0176810053.0838.3493810113.1539.2094710153.1938.7621910193.2441.40448
10203.2541.1434910213.26  43.96910233.2844.6416710243.2946.0946710263.3147.48283
10273.32 49.319510323.3854.6568210353.41 59.571110393.4564.9971110429.6468.49412
#Mann= 3 , 0 , 0
9808.527    0.04       09808.527    0.04       010429.64    0.04       0
#XS Ineff= 2 , 0
       0                               0
Bank Sta=9808.527,10429.64
Exp/Cntr=0.3,0.1

Type RM Length L Ch R = 1 ,22658.55,661.332900,661.332900,661.332900
XS GIS Cut Line= 6
854940.241117991853373.175929058855031.444567142853331.594890273
855123.056492742853280.965224429855318.623971532853165.600316036
 855470.87898461853061.989521259855572.888359042853012.148150273
#Sta/Elev= 30
9609.28154.348329669.20654.569329691.34653.874939743.85950.999569805.01744.60354
 9825.5643.66205 9887.0638.745359910.57837.612419934.09635.531819945.85431.97847
9991.83721.0590310003.1220.55805 10014.521.7848710025.8825.2041910041.3832.90689
   1004935.7772410060.9537.5640910113.5940.5456510148.1144.8735310170.8750.80231
10182.6352.9738510206.8752.4402810219.94 52.789210230.2954.5350210241.6659.96403
10264.3960.9334210286.69 63.051710308.7363.3908110330.7462.9853610339.2263.85677
#Mann= 3 , 0 , 0
9609.281    0.04       09609.281    0.04       010339.22    0.04       0
#XS Ineff= 2 , 0
       0                               0
Bank Sta=9609.281,10339.22
Exp/Cntr=0.3,0.1

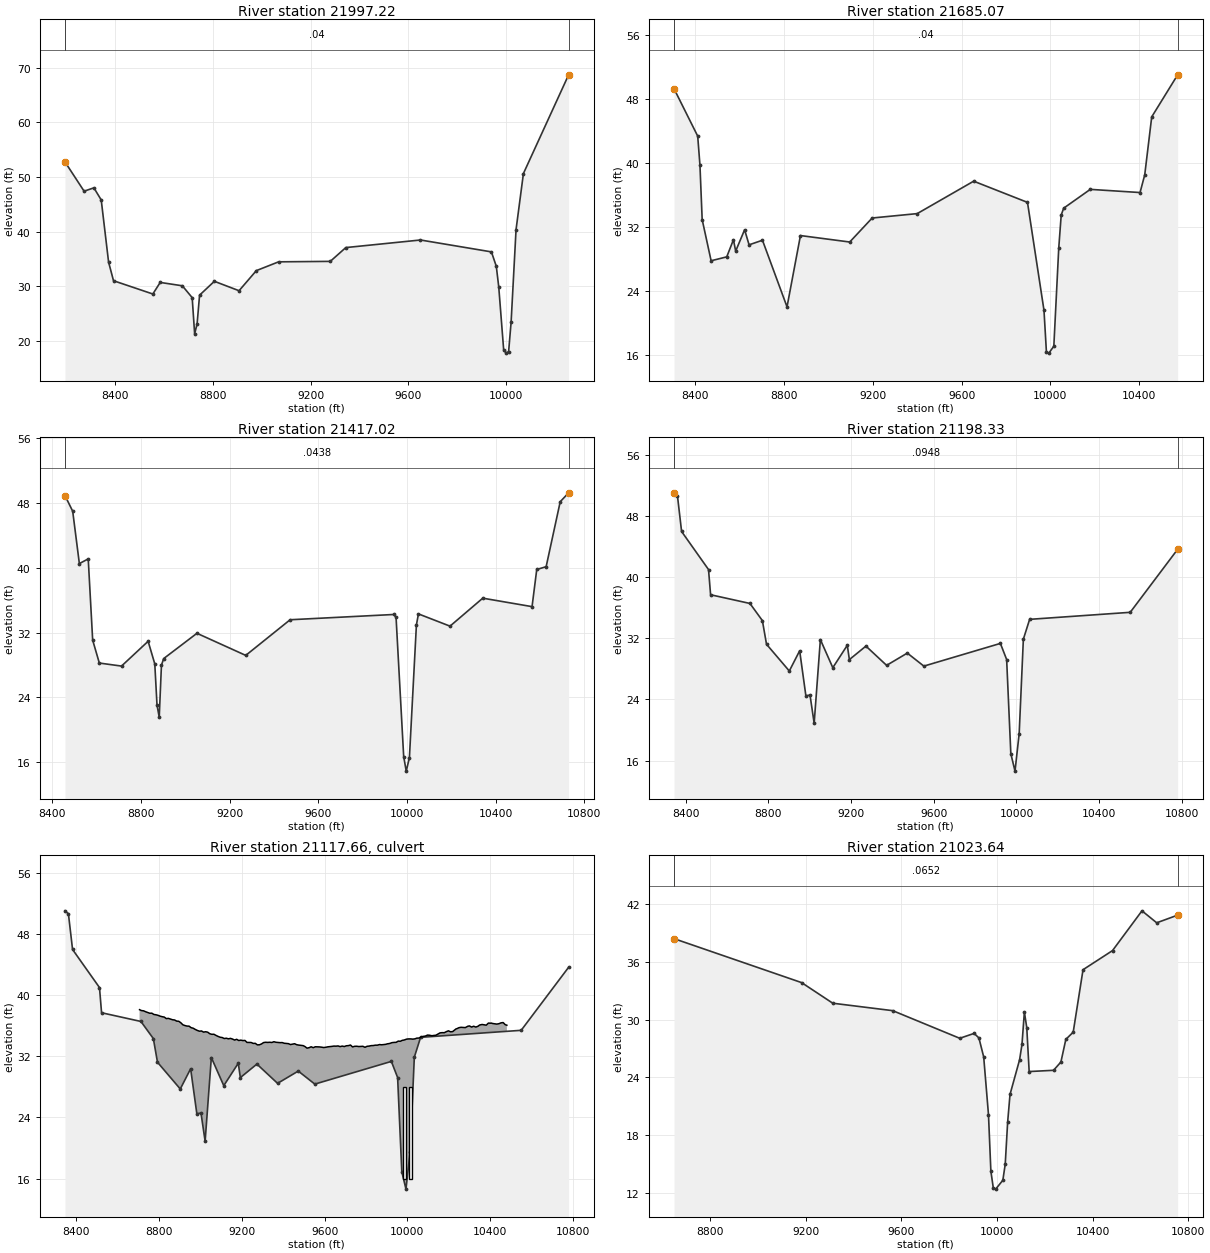
Type RM Length L Ch R = 1 ,21997.22,312.146100,312.146100,312.146100
XS GIS Cut Line= 6
853976.814394233853797.503176848854614.772255504853730.482543401
855144.497643123853634.958155313 855362.63037999853567.732441721
855600.150709475853415.651376369855969.441943648853445.882126856
#Sta/Elev= 30
8193.94852.778268272.27547.417498312.34748.030288342.40145.812428372.54234.44043
8392.67331.038228553.71728.610058583.91330.72819  8674.530.112568714.80627.94477
8724.89621.311328734.98523.158138745.07428.39963 8805.6130.933348906.68529.21039
8977.49232.887039068.69134.495329280.22734.578739343.88137.102799649.64738.49008
9940.088 36.31579960.09433.672239970.09629.880249990.25818.3745710000.39 17.7945
10010.5318.0908410020.6623.4428210040.9140.39425 10071.150.6515410256.16 68.7047
#Mann= 3 , 0 , 0
8193.948    0.04       08193.948    0.04       010256.16    0.04       0
#XS Ineff= 2 , 0
       09613.565                       0
Bank Sta=8193.948,10256.16
Exp/Cntr=0.3,0.1

Type RM Length L Ch R = 1 ,21685.07,268.056100,268.056100,268.056100
XS GIS Cut Line= 6
853979.010944136853885.971946517854700.943387228853799.509645979
 855489.28935367 853675.84436489855596.061392512853700.601224335
855921.055183927853840.747737475856186.647674187 853928.40691594
#Sta/Elev= 30
8303.74849.322868410.52443.395328420.59939.791458430.67332.96658 8470.9727.82186
8541.429 28.30848571.61230.450778581.67329.029278621.91731.696618642.03929.81188
8702.406 30.38698813.07822.060898873.55830.970619095.66830.163679196.82733.16333
9399.82133.712729654.20937.764169896.75335.116489971.07721.635739982.03216.44646
9993.18716.2807910015.4817.1498110037.6529.4096210048.7433.5364810059.8234.39044
10179.7236.7420410404.0836.3458710425.1538.5597110456.6445.79939 10573.551.05356
#Mann= 3 , 0 , 0
8303.748    0.04       08303.748    0.04       0 10573.5    0.04       0
#XS Ineff= 2 , 0
       09680.134        10167.28       0
Bank Sta=8303.748,10573.5
Exp/Cntr=0.3,0.1

Type RM Length L Ch R = 1 ,21417.02,218.683400,218.683400,218.683400
XS GIS Cut Line= 4
853980.167913442853911.367377925 855336.36041053853848.441877771
855686.790240656854046.123937148856170.806928728854214.740889669
#Sta/Elev= 30
8456.79548.905378491.66446.964988521.69740.51252 8561.7441.089798581.76131.07496
8611.79328.246048711.90127.87207 8832.0330.930668862.06228.139158872.073 23.0597
8882.08421.570028892.09527.978928902.10528.794289052.26731.915589272.50429.19014
9472.71933.58574 9939.1834.233519950.66133.907059985.10516.718689996.58714.91726
10010.97 16.574610042.5132.9386210051.6834.3065810194.1532.7955910341.9736.24659
10564.3435.2022310585.5239.7853610627.8840.1255510691.4248.1417510729.3349.23791
#Mann= 3 , 0 , 0
8456.795  0.0438       08456.795  0.0438       010729.33  0.0438       0
#XS Ineff= 2 , 0
       0 9797.47        10107.28       0
Bank Sta=8456.795,10729.33
Exp/Cntr=0.3,0.1

Type RM Length L Ch R = 1 ,21198.33,174.690300,174.690300,174.690300
XS GIS Cut Line= 5
853738.367266095854156.341288177854612.857727892854109.443378276
855318.442806082854117.898479789855747.348621353854179.487055666
856160.372126999854257.300545397
#Sta/Elev= 30
8344.36751.065228361.02450.677798381.05246.001678511.23941.014638521.25437.71633
8711.527 36.57488771.61334.330738791.64231.23142  8901.827.728538951.87230.37838
8981.91524.482249001.94324.575449021.97220.887739052.01531.842779112.10128.16308
9182.20231.100339192.21629.22176 9272.2630.990059372.26728.466929472.27530.07486
 9552.2828.368619922.30731.341939952.57929.230519972.78516.90184 9992.9914.61443
10013.1919.54224 10033.4 31.895410063.7134.4944510550.01 35.414710779.3443.67103
#Mann= 3 , 0 , 0
8344.367  0.0948       08344.367  0.0948       010779.34  0.0948       0
#XS Ineff= 2 , 0
       09944.173        10058.69       0
Bank Sta=8344.367,10779.34
Exp/Cntr=0.3,0.1

Type RM Length L Ch R = 2 ,21117.66,,,
Bridge Culvert--1,0,-1,-1, 0
Deck Dist Width WeirC Skew NumUp NumDn MinLoCord MaxHiCord MaxSubmerge Is_Ogee
27.345,120,2.6,0,195,195, , , 0.95, 0, 0,0,,
 8704.97 8714.25 8724.25 8734.26 8744.26 8754.27 8764.27 8767.27 8774.27 8784.28
 8794.28 8804.28 8814.29 8824.29 8834.30 8844.30 8854.30 8864.31 8874.31 8884.31
 8894.32 8904.32 8914.33 8924.33 8934.33 8944.34 8954.34 8964.34 8974.35 8984.35
 8994.36 9004.36 9014.36 9024.37 9034.37 9044.37 9054.38 9064.38 9074.39 9084.39
 9094.39 9104.40 9114.40 9124.40 9131.62 9134.41 9144.41 9154.42 9164.42 9174.42
 9184.43 9194.43 9204.43 9214.44 9224.44 9234.45 9244.45 9254.45 9264.46 9274.46
 9284.46 9294.47 9304.47 9314.48 9324.48 9334.48 9344.49 9354.49 9364.49 9374.50
 9384.50 9394.51 9404.51 9414.51 9424.52 9434.52 9444.53 9454.53 9464.53 9474.54
 9484.54 9494.54 9495.97 9504.55 9514.55 9524.56 9534.56 9544.56 9554.57 9564.57
 9574.57 9584.58 9594.58 9604.59 9614.59 9624.59 9634.60 9642.77 9644.60 9654.61
 9664.62 9674.63 9684.64 9694.65 9704.66 9714.67 9724.68 9731.89 9734.69 9744.70
 9754.71 9764.72 9774.73 9784.74 9794.76 9804.77 9814.78 9824.79 9834.80 9844.81
 9854.82 9864.83 9874.84 9884.85 9886.08 9894.94 9905.04 9907.52 9915.14 9925.24
 9935.34 9945.44 9955.55 9965.65 9975.75 9978.31 9985.85 9995.9510006.0510016.15
10026.2510036.3610046.4610049.0910056.5610066.6610076.7610086.8610096.9610107.06
10117.1710119.8810123.2110127.2910137.4510147.6010157.7610167.9210177.7010178.07
10188.2310198.3910208.5410218.7010228.8510234.8810239.0110249.1710259.3210269.48
10279.6410289.7910292.0610299.9510310.1110320.2610330.4210340.5810349.2410350.73
10360.8910371.0510381.2010391.3610401.5210406.4210411.6710421.8310431.9910442.14
10452.3010462.4510463.6010472.6110480.81
   38.12   38.00   37.97   37.85   37.75   37.65   37.66   37.61   37.49   37.45
   37.38   37.27   37.20   37.15   36.95   36.98   36.89   36.80   36.77   36.62
   36.60   36.41   36.14   36.04   35.97   35.96   35.76   35.69   35.53   35.40
   35.30   35.33   35.18   35.23   35.17   34.97   34.89   34.90   34.75   34.62
   34.51   34.47   34.34   34.38   34.32   34.30   34.36   34.27   34.14   34.24
   34.08   34.13   34.07   34.09   33.83   33.83   33.82   33.70   33.71   33.51
   33.52   33.63   33.81   33.85   33.83   33.85   33.82   33.92   33.85   33.83
   33.80   33.81   33.72   33.69   33.67   33.55   33.60   33.66   33.53   33.48
   33.45   33.43   33.41   33.29   33.08   33.14   33.26   33.14   33.26   33.25
   33.24   33.21   33.16   33.19   33.25   33.28   33.31   33.35   33.35   33.34
   33.37   33.28   33.35   33.29   33.39   33.41   33.49   33.31   33.24   33.32
   33.33   33.29   33.31   33.32   33.19   33.32   33.35   33.41   33.42   33.47
   33.47   33.55   33.52   33.54   33.55   33.58   33.66   33.66   33.70   33.80
   33.83   33.84   34.00   33.98   34.11   34.11   34.16   34.26   34.29   34.29
   34.26   34.30   34.40   34.39   34.41   34.54   34.62   34.66   34.79   34.77
   34.71   34.71   34.73   34.74   34.77   34.92   35.08   35.11   35.10   35.10
   35.24   35.35   35.22   35.25   35.48   35.60   35.63   35.76   35.81   35.79
   35.77   35.91   35.95   35.99   35.84   35.95   35.84   35.94   36.11   36.12
   36.18   36.14   36.09   36.36   36.35   36.36   36.31   36.27   36.23   36.28
   36.39   36.43   36.41   36.16   36.08
                                                                                
                                                                                
                                                                                
                                                                                
                                                                                
                                                                                
                                                                                
                                                                                
                                                                                
                                                                                
                                                                                
                                                                                
                                                                                
                                                                                
                                                                                
                                                                                
                                                                                
                                                                                
                                                                                
                                        
 8704.97 8714.25 8724.25 8734.26 8744.26 8754.27 8764.27 8767.27 8774.27 8784.28
 8794.28 8804.28 8814.29 8824.29 8834.30 8844.30 8854.30 8864.31 8874.31 8884.31
 8894.32 8904.32 8914.33 8924.33 8934.33 8944.34 8954.34 8964.34 8974.35 8984.35
 8994.36 9004.36 9014.36 9024.37 9034.37 9044.37 9054.38 9064.38 9074.39 9084.39
 9094.39 9104.40 9114.40 9124.40 9131.62 9134.41 9144.41 9154.42 9164.42 9174.42
 9184.43 9194.43 9204.43 9214.44 9224.44 9234.45 9244.45 9254.45 9264.46 9274.46
 9284.46 9294.47 9304.47 9314.48 9324.48 9334.48 9344.49 9354.49 9364.49 9374.50
 9384.50 9394.51 9404.51 9414.51 9424.52 9434.52 9444.53 9454.53 9464.53 9474.54
 9484.54 9494.54 9495.97 9504.55 9514.55 9524.56 9534.56 9544.56 9554.57 9564.57
 9574.57 9584.58 9594.58 9604.59 9614.59 9624.59 9634.60 9642.77 9644.60 9654.61
 9664.62 9674.63 9684.64 9694.65 9704.66 9714.67 9724.68 9731.89 9734.69 9744.70
 9754.71 9764.72 9774.73 9784.74 9794.76 9804.77 9814.78 9824.79 9834.80 9844.81
 9854.82 9864.83 9874.84 9884.85 9886.08 9894.94 9905.04 9907.52 9915.14 9925.24
 9935.34 9945.44 9955.55 9965.65 9975.75 9978.31 9985.85 9995.9510006.0510016.15
10026.2510036.3610046.4610049.0910056.5610066.6610076.7610086.8610096.9610107.06
10117.1710119.8810123.2110127.2910137.4510147.6010157.7610167.9210177.7010178.07
10188.2310198.3910208.5410218.7010228.8510234.8810239.0110249.1710259.3210269.48
10279.6410289.7910292.0610299.9510310.1110320.2610330.4210340.5810349.2410350.73
10360.8910371.0510381.2010391.3610401.5210406.4210411.6710421.8310431.9910442.14
10452.3010462.4510463.6010472.6110480.81
   38.12   38.00   37.97   37.85   37.75   37.65   37.66   37.61   37.49   37.45
   37.38   37.27   37.20   37.15   36.95   36.98   36.89   36.80   36.77   36.62
   36.60   36.41   36.14   36.04   35.97   35.96   35.76   35.69   35.53   35.40
   35.30   35.33   35.18   35.23   35.17   34.97   34.89   34.90   34.75   34.62
   34.51   34.47   34.34   34.38   34.32   34.30   34.36   34.27   34.14   34.24
   34.08   34.13   34.07   34.09   33.83   33.83   33.82   33.70   33.71   33.51
   33.52   33.63   33.81   33.85   33.83   33.85   33.82   33.92   33.85   33.83
   33.80   33.81   33.72   33.69   33.67   33.55   33.60   33.66   33.53   33.48
   33.45   33.43   33.41   33.29   33.08   33.14   33.26   33.14   33.26   33.25
   33.24   33.21   33.16   33.19   33.25   33.28   33.31   33.35   33.35   33.34
   33.37   33.28   33.35   33.29   33.39   33.41   33.49   33.31   33.24   33.32
   33.33   33.29   33.31   33.32   33.19   33.32   33.35   33.41   33.42   33.47
   33.47   33.55   33.52   33.54   33.55   33.58   33.66   33.66   33.70   33.80
   33.83   33.84   34.00   33.98   34.11   34.11   34.16   34.26   34.29   34.29
   34.26   34.30   34.40   34.39   34.41   34.54   34.62   34.66   34.79   34.77
   34.71   34.71   34.73   34.74   34.77   34.92   35.08   35.11   35.10   35.10
   35.24   35.35   35.22   35.25   35.48   35.60   35.63   35.76   35.81   35.79
   35.77   35.91   35.95   35.99   35.84   35.95   35.84   35.94   36.11   36.12
   36.18   36.14   36.09   36.36   36.35   36.36   36.31   36.27   36.23   36.28
   36.39   36.43   36.41   36.16   36.08
                                                                                
                                                                                
                                                                                
                                                                                
                                                                                
                                                                                
                                                                                
                                                                                
                                                                                
                                                                                
                                                                                
                                                                                
                                                                                
                                                                                
                                                                                
                                                                                
                                                                                
                                                                                
                                                                                
                                        
BR Coef=-1 , 0 , 0 ,, 0 ,,,0.8,-1,,0,
WSPro=,,,, 1 ,,,, 0 ,,,, 0 ,,,,-1 ,-1 ,-1 , 0 , 0 , 0 , 0 , 0
Multiple Barrel Culv=2,12,15,120,0.013,0.5,1,8,3,16,14,2,Culvert #1, 0, 27.345
 9985.00 9985.0010015.0010015.00
Culvert Bottom n=0.013
BC Design=,, 0 ,, 0 ,,,,,,

Type RM Length L Ch R = 1 ,21023.64,482.090800,482.090800,482.090800
XS GIS Cut Line= 5
 854011.18561577 854246.60589687854501.926722508 854241.99390279
854968.681234724854278.961144901855521.797681408 854308.97448606
856100.266803433854445.942592164
#Sta/Elev= 30
8648.68838.440259182.65933.861529313.06631.716019563.84930.941269844.33328.06438
9904.42228.574539924.45128.101379944.48126.12391 9964.5120.121999974.52514.22573
9984.53912.507219994.55412.35866 10024.6 13.280410034.6114.9555410044.6319.30746
10054.6422.21944 10094.725.8305810104.7227.4310210114.7330.8073610124.7529.16257
10134.7624.6015610236.8224.7320810267.6525.5989210288.2127.9542810319.0428.70398
10360.1435.2052510483.46 37.195610606.7841.3369910668.44 40.090110756.0640.88861
#Mann= 3 , 0 , 0
8648.688  0.0652       08648.688  0.0652       010756.06  0.0652       0
#XS Ineff= 2 , 0
       09928.716        10070.53       0
Bank Sta=8648.688,10756.06
Exp/Cntr=0.3,0.1

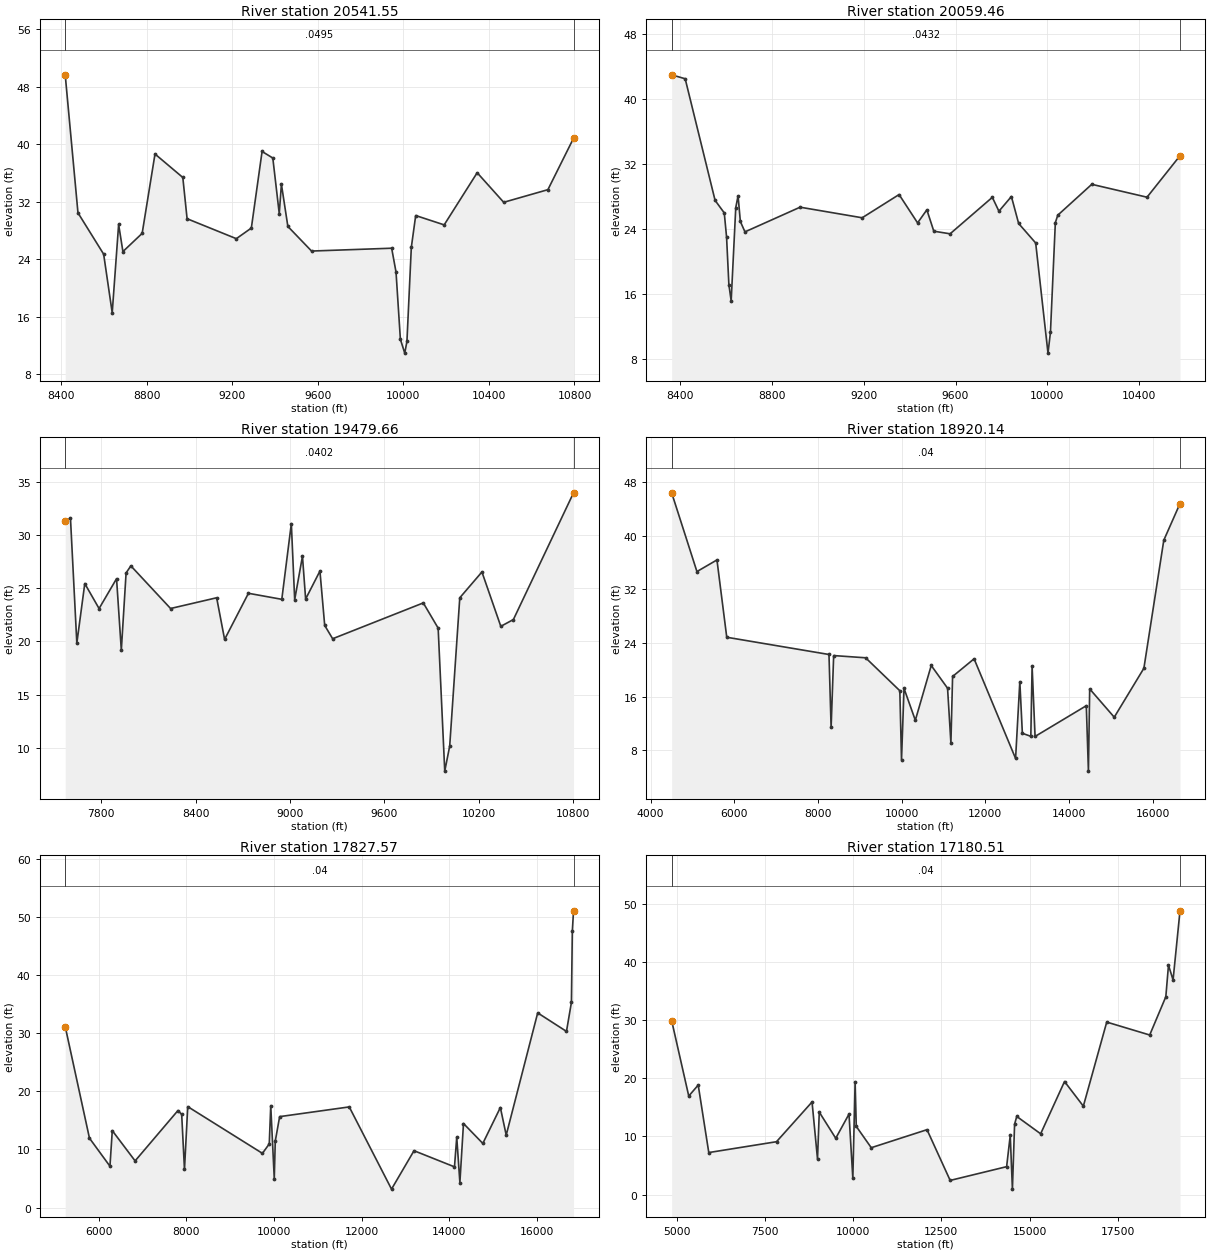
Type RM Length L Ch R = 1 ,20541.55,482.090700,482.090700,482.090700
XS GIS Cut Line= 6
 853715.40366761854667.876746625854349.499641109854660.295763617
854563.053294918854671.497680536854899.967018371854706.153119043
855296.825564019854771.819439281856060.989365694854960.564955144
#Sta/Elev= 30
8419.04449.637098478.71130.454358598.77824.71129  8638.8 16.56358668.81728.84298
8688.82425.068678778.827 27.60298838.82838.630748968.84735.370978988.85129.63662
9219.09126.863939289.24128.340179339.43338.984259389.62538.07263 9419.7430.34215
9429.77934.438779459.967 28.5653 9570.7325.143849945.25625.538299965.63722.22418
9986.01912.8806810006.4210.9562310016.6612.5833810037.1425.6520810057.62 30.0805
10190.7528.7814810345.0536.0299510469.0531.9187110675.71 33.675310795.5140.82438
#Mann= 3 , 0 , 0
8419.044  0.0495       08419.044  0.0495       010795.51  0.0495       0
#XS Ineff= 2 , 0
       09801.297        10238.87       0
Bank Sta=8419.044,10795.51
Exp/Cntr=0.3,0.1

Type RM Length L Ch R = 1 ,20059.46,579.797700,579.797700,579.797700
XS GIS Cut Line= 6
853536.306754581855078.875720891854167.605071147855065.197262542
854754.313629282855121.533557475855084.755248826 855205.88227078
855347.657431367 855299.94438942855685.033654052855453.351226851
#Sta/Elev= 30
8364.26843.010448423.067 42.52568553.23327.54777 8593.2725.999618603.27223.01346
8613.27417.179878623.27615.16069 8643.28 26.65878653.28228.110258663.284 24.9458
8683.28823.666768923.32426.706949193.61125.403039354.265 28.26389434.82124.77365
9475.18726.381539505.46823.750529576.38323.428129760.25227.920859788.95826.21148
9843.24728.021429874.80624.698849948.96422.2982510002.548.73193510013.2111.27278
10034.5524.8045210045.2125.7236510193.1729.5246210433.6927.9373110577.2433.04404
#Mann= 3 , 0 , 0
8364.268  0.0432       08364.268  0.0432       010577.24  0.0432       0
#XS Ineff= 2 , 0
       09494.316        10204.81       0
Bank Sta=8364.268,10577.24
Exp/Cntr=0.3,0.1

Type RM Length L Ch R = 1 ,19479.66,559.525800,559.525800,559.525800
XS GIS Cut Line= 5
852671.831293296855376.127318375854911.568571841855700.047587419
855084.154206196855754.970211907 855156.06698781855781.987024177
855867.249978001855804.433225763
#Sta/Elev= 30
7570.65131.274217604.16531.564087644.58119.834687695.10125.432687786.037 23.0851
7897.18225.892177927.49419.173247957.80626.431147988.11827.096048240.71923.08984
8533.73624.098368584.25620.187368735.81724.519048948.00223.952339008.62631.06369
9029.92123.912869079.35427.998719099.56223.982439190.49926.607739220.81121.50065
9271.33120.249679847.78523.615089942.23321.248659984.2097.81521310015.7110.17249
 10079.8 24.096810220.6226.5209310340.6821.4154110420.7222.0524910803.1633.95509
#Mann= 3 , 0 , 0
7570.651  0.0402       07570.651  0.0402       010803.16  0.0402       0
#XS Ineff= 2 , 0
       09027.423        10443.68       0
Bank Sta=7570.651,10803.16
Exp/Cntr=0.3,0.1

Type RM Length L Ch R = 1 ,18920.14,1092.568200,1092.568200,1092.568200
XS GIS Cut Line= 6
849591.997231306857254.593439463854385.287039268856340.574808348
855115.480761027856267.135126766855519.559966332856265.543434257
856408.684561395856235.858691375861587.708525803855431.041981049
#Sta/Elev= 30
4504.51446.403275108.202 34.64945586.67136.387625820.81524.846378264.059 22.2734
 8314.9611.380338376.04122.112979139.55521.780449957.11516.864049997.3186.559399
10057.5217.2106310327.6812.4542510707.74 20.630911097.9817.2422411178.039.050683
11218.0618.9902211731.9821.6300112723.756.75270212824.9518.2259612885.6710.50968
13088.0710.0617813118.4320.5289113189.2710.0408414413.79 14.628214464.394.864905
14494.7517.1364915081.7112.9126215790.1120.2189516265.76 39.328216653.0644.80489
#Mann= 3 , 0 , 0
4504.514    0.04       04504.514    0.04       016653.06    0.04       0
#XS Ineff= 2 , 0
       08577.851         10867.1       0
Bank Sta=4504.514,16653.06
Exp/Cntr=0.3,0.1

Type RM Length L Ch R = 1 ,17827.57,647.062700,647.062700,647.062700
XS GIS Cut Line= 6
850994.363442086858953.062950863854264.183820149857771.216616795
854943.794505874857484.883072672855567.060154625857180.342950753
856154.278094831856970.028143229862061.898379317 855572.63926146
#Sta/Elev= 30
5231.39831.154265784.999 11.94436252.8587.1148166306.02413.240986827.0488.033208
7805.29816.699737890.363 16.03697954.1626.5570728028.59417.370679733.7429.329889
9889.41810.95667 9923.5217.5436610003.83   4.97610026.6511.4392710126.5215.64837
 11715.517.3202812680.573.17601513193.919.78633314117.917.00668514169.2412.11466
14241.114.30472314323.2414.4662214764.7111.0386515165.1217.2175915298.5812.47025
16017.25 33.496516674.3230.3111916787.2635.3092316807.7947.5415116835.41 51.0559
#Mann= 3 , 0 , 0
5231.398    0.04       05231.398    0.04       016835.41    0.04       0
#XS Ineff= 2 , 0
       07588.427        10881.88       0
Bank Sta=5231.398,16835.41
Exp/Cntr=0.3,0.1

Type RM Length L Ch R = 1 ,17180.51,957.386500,957.386500,957.386500
XS GIS Cut Line= 6
850896.115016063859374.087851126853859.147571149 858615.55651079
856363.592028438857538.340933849 857057.44798827857301.027614104
862601.459930086856023.251727154864636.844973575855189.525342094
#Sta/Elev= 30
 4856.6629.921655340.66516.95322 5609.0518.842265908.401 7.227997828.3829.094797
8835.61615.931458990.6036.1100339040.27214.184479507.1349.6877399883.03513.84667
9991.5552.796296 10056.619.4183710089.1111.7305410513.928.06224412094.1611.16424
12750.692.43363914350.98  4.799614453.5610.1873214515.110.93573514576.6612.10647
14638.2113.4429615315.2510.45676 15992.319.4507316525.7315.2107617188.4829.67733
18406.6427.4544918863.47 34.032818939.1239.4758519068.7936.92068 19265.348.82045
#Mann= 3 , 0 , 0
 4856.66    0.04       0 4856.66    0.04       0 19265.3    0.04       0
#XS Ineff= 2 , 0
       07231.684        10851.18       0
Bank Sta=4856.66,19265.3
Exp/Cntr=0.3,0.1

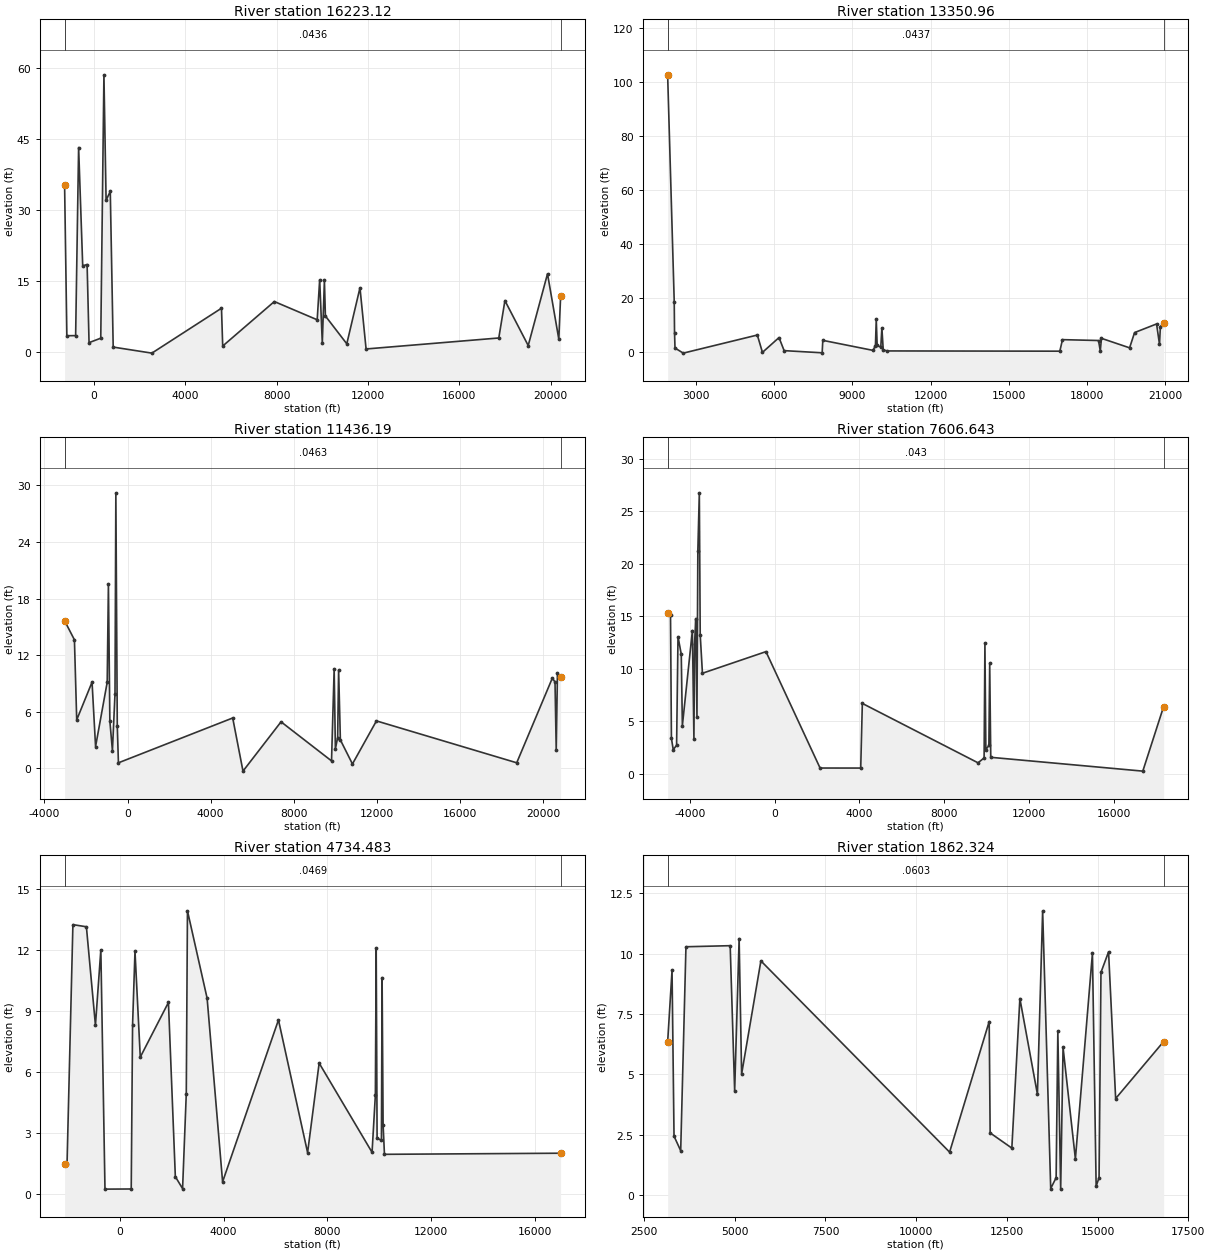
Type RM Length L Ch R = 1 ,16223.12,2872.159300,2872.159300,2872.159300
XS GIS Cut Line= 6
845562.008091166862499.437106849853809.760384754859426.796469961
854824.586575116859079.818521126855953.065076115858741.949655887
856557.666480739858512.916029118866271.025657561 856113.09416119
#Sta/Elev= 30
 -1278.435.19815-1179.153.365659-794.9373.387184-664.63843.10709-485.43218.11559
-293.32618.40169-207.9451.905111304.33892.844976443.082658.45598537.4815 31.9653
720.569833.84928848.64090.9662462541.013-0.310045587.2699.1710635640.6321.188945
7899.94610.581789775.7426.7304669884.03315.19244    9999 1.8098310091.1315.03948
10134.267.53376311070.751.65691111647.4213.4861511914.740.56789517722.342.888199
17990.1210.7770619009.741.29011819854.2616.4431420348.622.64300420426.9111.64825
#Mann= 3 , 0 , 0
 -1278.4  0.0436       0 -1278.4  0.0436       020426.91  0.0436       0
#XS Ineff= 2 , 0
       06949.279        10944.85       0
Bank Sta=-1278.4,20426.91
Exp/Cntr=0.3,0.1

Type RM Length L Ch R = 1 ,13350.96,1914.772900,1914.772900,1914.772900
XS GIS Cut Line= 6
849605.891930849865256.094776092855165.159434655862079.153212985
856141.181266682861614.957736946857667.073722101861051.313061596
859609.829894758859980.188415196866446.570354785856473.804506375
#Sta/Elev= 30
1921.156102.80942174.08318.721342185.6267.2883382203.6051.5710262520.387-0.31004
5360.0836.3969345556.322-0.035076191.2135.4533446387.4520.6136527845.699-0.18766
7870.7194.4259879794.6970.7078069888.7822.4856819919.71912.251129954.4222.549558
10093.841.893492 10135.29.08392510187.380.89584710335.110.50243516958.310.412419
17059.464.68634218441.79   4.36518509.230.49197418554.185.17002819633.081.650832
19824.13 7.3058120667.0110.50148 20779.42.97800920813.119.489005 20938.511.00952
#Mann= 3 , 0 , 0
1921.156  0.0437       01921.156  0.0437       0 20938.5  0.0437       0
#XS Ineff= 2 , 0
       06944.638        11954.44       0
Bank Sta=1921.156,20938.5
Exp/Cntr=0.3,0.1

Type RM Length L Ch R = 1 ,11436.19,3829.545800,3829.545800,3829.545800
XS GIS Cut Line= 6
848620.679288492872081.583096558856111.894720185 865001.28652652
858563.569656633 861882.25585292 859396.59313048861036.004507374
860321.788008798860301.385757968866495.196190286856573.721634039
#Sta/Elev= 30
-3028.4515.66234-2555.1713.63972 -2445.25.153872-1707.099.153885   -15382.322052
-978.3379.138452-920.03619.58635 -850.725.027854 -727.011.896903  -603.37.921602
-562.06429.22174-493.336 4.48895-438.3540.6000685059.8635.3526755554.703 -0.2815
7385.9384.9462639814.3750.8028039941.36410.57422   100002.08257310108.963.282808
 10155.610.4349710240.193.02672310820.690.477684 11975.65.04273218724.440.602072
20438.279.57878620566.769.16622320625.171.93874220683.5710.0706920835.669.719419
#Mann= 3 , 0 , 0
-3028.45  0.0463       0-3028.45  0.0463       020835.66  0.0463       0
#XS Ineff= 2 , 0
       06550.298         12087.2       0
Bank Sta=-3028.45,20835.66
Exp/Cntr=0.3,0.1

Type RM Length L Ch R = 1 ,7606.643,2872.159400,2872.159400,2872.159400
XS GIS Cut Line= 6
850324.890909082875369.718156469857925.858674285  867964.9038988
860569.492202892865256.419123917861594.012878345  864404.5723693
863900.541803134862326.770101529867491.380050802859535.349907713
#Sta/Elev= 30
-5040.6515.27264-4904.9215.10604-4861.923.383801-4775.942.301737 -4618.32.731561
-4551.8713.06539 -4398.3 11.3958-4346.024.598175-3873.1113.64633-3801.463.312047
-3770.0612.38052-3715.47 14.7905-3658.155.459551-3616.4921.24409-3546.6926.75476
-3504.81 13.2454 -3400.29.581811-405.49211.638312145.7620.5600734061.9870.556917
4137.7226.7105959591.9071.0569659878.3041.520837 9916.8812.455899960.5342.312296
10103.772.705847 10142.110.5116710192.261.57979517360.170.26512418342.386.416405
#Mann= 3 , 0 , 0
-5040.65   0.043       0-5040.65   0.043       018342.38   0.043       0
#XS Ineff= 2 , 0
       0 5840.43        11166.91       0
Bank Sta=-5040.65,18342.38
Exp/Cntr=0.3,0.1

Type RM Length L Ch R = 1 ,4734.483,2872.159300,2872.159300,2872.159300
XS GIS Cut Line= 6
853653.943546885874859.466601465859457.796884534869769.237459016
860450.238391349868930.758214183862461.215206021867397.418397179
863869.193511331866260.829450478868441.291102555 862739.28250203
#Sta/Elev= 30
-2133.641.464564-2039.131.464564-1813.0113.22883-1292.7413.12309-943.9298.280028
 -735.61 11.9889-575.9960.217847436.1638 0.22486488.0978 8.29152581.206111.92279
784.97846.710721 1871.429.4013412137.4440.8322322416.768 0.243112559.3834.909065
 2604.8813.907593363.1739.6055433959.7050.5762316114.0968.5396787238.0772.013238
7683.6366.416425 9724.09 2.027279851.7134.8523069883.61912.055379918.3372.713133
10085.322.62844710111.2110.6232510150.093.38491310201.92 1.9300216995.211.984424
#Mann= 3 , 0 , 0
-2133.64  0.0469       0-2133.64  0.0469       016995.21  0.0469       0
#XS Ineff= 2 , 0
       06289.052        11409.29       0
Bank Sta=-2133.64,16995.21
Exp/Cntr=0.3,0.1

Type RM Length L Ch R = 1 ,1862.324,1862.323900,1862.323900,1862.323900
XS GIS Cut Line= 6
858926.370280561873880.952516888862575.421191528870551.268934691
863602.648831217869782.397170738 864483.16559602869335.099642388
865037.381458259868958.821804657 869488.39534743865259.131528954
#Sta/Elev= 30
3150.869 6.321813272.2729.3027073327.0642.4326593510.7641.8284533655.81110.28345
4874.91510.328174998.1944.3083565121.47210.622775189.9615.0055455721.353 9.69772
10922.681.769581 12014.17.18471112040.022.56685712638.091.93665912859.778.137704
13343.254.17033513487.1811.7730113709.620.260795   138590.70986613905.886.789521
13984.390.23589214049.816.10865414389.88 1.4889814859.8410.0191814961.980.359354
 15042.60.71286315094.829.22088815304.2310.07239 15499.53.990915 16822.46.354618
#Mann= 3 , 0 , 0
3150.869  0.0603       03150.869  0.0603       0 16822.4  0.0603       0
#XS Ineff= 2 , 0
       07688.956        12310.13       0
Bank Sta=3150.869,16822.4
Exp/Cntr=0.3,0.1

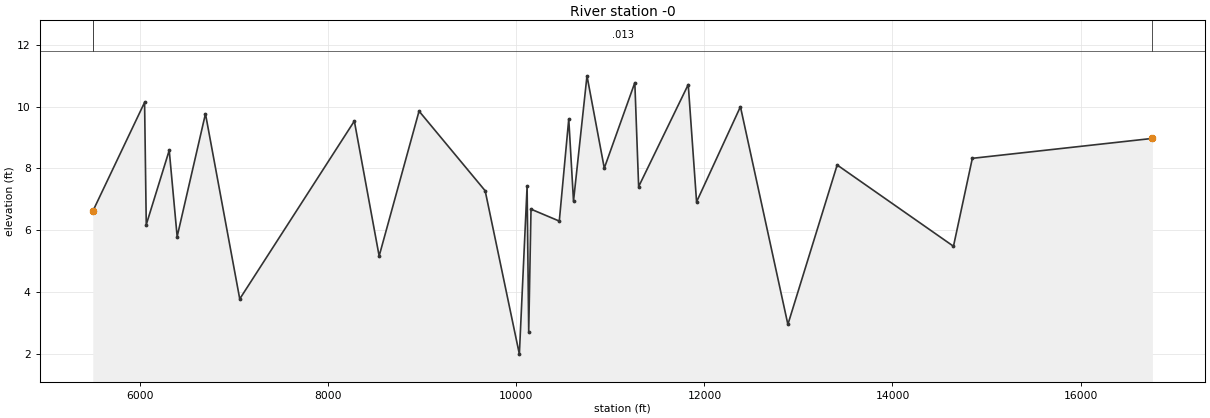
Type RM Length L Ch R = 1 ,      -0,0.000000,0.000000,0.000000
XS GIS Cut Line= 6
862869.911078913 873931.99298617864136.467364674 873082.06063896
865793.143943303870342.674790875868090.020801058869361.084187801
869092.208439907866812.937988484869918.875276903865990.231740387
#Sta/Elev= 30
5495.4796.6118376046.41410.13535 6064.366.1793426308.4838.5835876392.7835.791738
6693.8569.766944 7058.483.7746538277.0969.5312568540.9185.1633468965.2239.852756
9668.2467.27570710031.991.98900910114.217.41863710131.382.716672 10155.96.679935
10456.566.29435910557.319.59638610607.69 6.9400310751.1410.9949610935.138.007765
11259.8310.7741411300.457.40869811827.8810.7124211916.476.91640812382.939.995842
12887.64 2.9501613411.588.10997114648.455.47948114849.158.32519516764.268.969709
#Mann= 3 , 0 , 0
5495.479   0.013       05495.479   0.013       016764.26   0.013       0
#XS Ineff= 2 , 0
       07922.849        12046.03       0
Bank Sta=5495.479,16764.26
Exp/Cntr=0.3,0.1